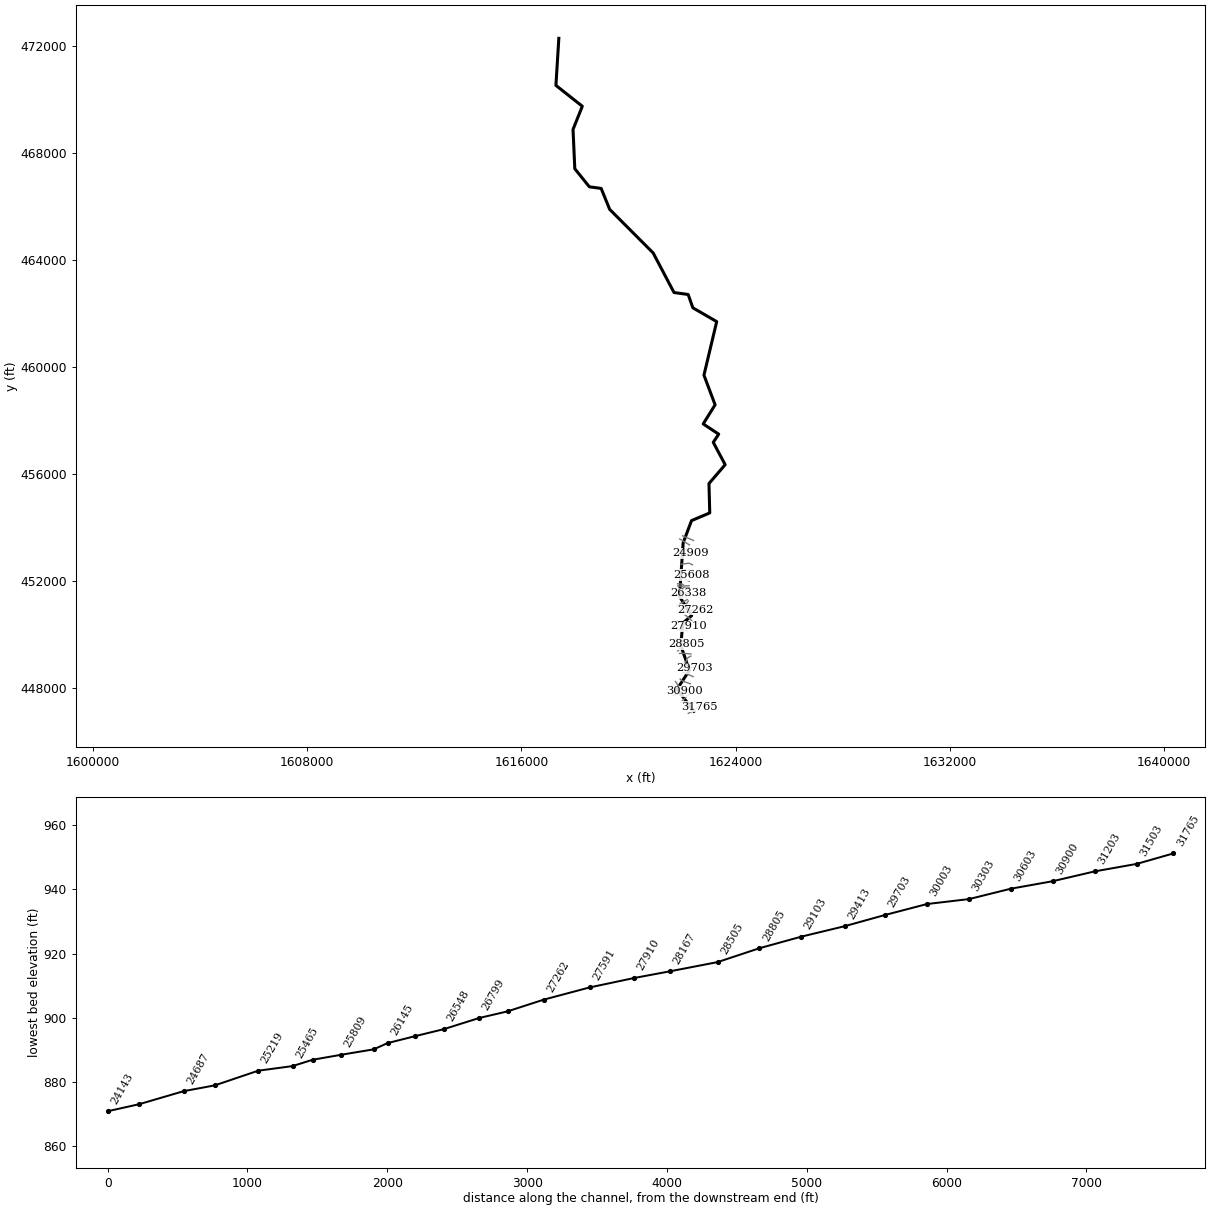
--- WhtstneCrk.prj (project) ---

Proj Title=WhtstneCrk
Current Plan=p01
Default Exp/Contr=0,0
English Units
Geom File=g01
Flow File=f01
Plan File=p01
BEGIN DESCRIPTION:
---------- MODELED AS PART OF WVEM CTP PROGRAM, 2025----------
Stream Name: Whetstone Creek
Flood Zone: AFH
Marshall County, WV
HEC-RAS Version: RAS 6.6
Vertical Datum: NAVD88
Projection: NAD 1983 StatePlane West Virginia N FIPS 4701 (US Feet)
Terrain: 1-meter West Virginia FEMA R3 South Central (collected 2018-2019)
Land Use: 2024 NLCD
Hydrologic Method:
Duda et al., "Estimation of magnitude and frequency of floods for rural, unregulated streams in and near Virginia and West Virginia." September 8, 2025.
Additional Model Notes:
None
END DESCRIPTION:
DSS Export Rating Curves= 0
DSS Export Rating Curve Sorted= 0
DSS Export Volume Flow Curves= 0
DXF OffsetX= 0
DXF OffsetY= 0
DXF ScaleX= 0
DXF ScaleY= 0

--- WhtstneCrk.p01 (plan) ---

Plan Title=Floodplain
Program Version=6.60
Short Identifier=Floodplain
Geom File=g01
Flow File=f01
Subcritical Flow
K Sum by GR= 0
Std Step Tol= 0.01
Critical Tol= 0.01
Num of Std Step Trials= 20
Max Error Tol= 0.3
Flow Tol Ratio= 0.001
Split Flow NTrial= 30
Split Flow Tol= 0.02
Split Flow Ratio= 0.02
Log Output Level= 0
Friction Slope Method= 1
Unsteady Friction Slope Method= 2
Unsteady Bridges Friction Slope Method= 1
Parabolic Critical Depth
Global Vel Dist= 0 , 0 , 0
Global Log Level= 0
CheckData=False
Encroach Param=-1 ,0,0, 0
Flow Ratio Tolerance=0.1
Flow Ratio Min Ratio=0.5
Flow Ratio Max Ratio=4
Flow Ratio Max Iterations= 10
Mapping Interval=1HOUR
Computation Time Step Use Courant=        0
Computation Time Step Use Time Series=    0
Computation Time Step Count To Double=0
Computation Time Step Max Doubling=0
Computation Time Step Max Halving=0
Computation Time Step Residence Courant=0
Run HTab= 0
Run UNet= 0
Run Sediment= 0
Run PostProcess= 0
Run WQNet= 0
Run RASMapper=-1
UNET Theta= 0
UNET Theta Warmup= 0
UNET ZTol= 0
UNET ZSATol= 0
UNET MxIter= 0
UNET Max Iter WO Improvement= 0
UNET MaxInSteps= 0
UNET DtIC= 0
UNET DtMin= 0
UNET MaxCRTS= 0
UNET WFStab= 0
UNET SFStab= 0
UNET WFX= 1
UNET SFX= 1
UNET Gravity=32.17405
UNET 1D Methodology=Finite Difference
UNET DSS MLevel= 1
UNET Pardiso=0
UNET DZMax Abort= 0
UNET Use Existing IB Tables= 0
UNET Froude Reduction=False
UNET Froude Limit= 0
UNET Froude Power= 0
UNET D1 Cores= 0
UNET WindReference=Eulerian
UNET WindDragFormulation=Hsu (1988)
UNET D2 Coriolis=0
UNET D2 Cores= 0
UNET D2 Theta= 1
UNET D2 Theta Warmup= 1
UNET D2 Z Tol= 0.01
UNET D2 Volume Tol= 0.01
UNET D2 Max Iterations= 20
UNET D2 Advanced Convergence=0
UNET D2 WS Max Tol=0.15
UNET D2 WS RMS Tol=0.002
UNET D2 WS Stall Tol=1
UNET D2 Equation= 0
UNET D2 RampUpFraction=0.1
UNET D2 TimeSlices= 1
UNET D2 Turbulence Formulation=Non-Conservative (original)
UNET D2 Eddy Viscosity=0.3
UNET D2 Transverse Eddy Viscosity=0.1
UNET D2 Smagorinsky Mixing=0
UNET D2 BCVolumeCheck=0
UNET D2 Cores=0
UNET D2 SolverType=PARDISO (Direct)
UNET D2 Minimum Iterations= 3
UNET D2 Maximum Iterations= 30
UNET D2 Restart Number= 10
UNET D2 Relaxation Coeff=1.3
UNET D2 SOR Precondition Iterations= 10
UNET D2 ILUT Maximum Fill= 8
UNET D2 ILUT Tolerance=1E-08
UNET D2 Convergence Tolerance=0.00001
PS Theta= 1
PS WS Tol= 0.01
PS Volume Tol= 0.01
PS Max Iterations= 20
PS Equation= 0
PS Advance Time Step=-1
PS Target Courant=0.9
PS Time Slices= 1
PS Iterate With 2D=0
PS Project Initial WSE from DS=-1
PS Ramp Up Initial WSE from US=-1
PS Cores=0
UNET D1D2 MaxIter= 0
UNET D1D2 ZTol=0.01
UNET D1D2 QTol=0.1
UNET D1D2 MinQTol=1
Write IC File= 0
Write IC File at Fixed DateTime=0
Write IC File at Sim End=0
Echo Input=False
Echo Parameters=False
Echo Output=False
Write Detailed= 0
HDF Write Warmup=0
HDF Write Time Slices=0
HDF Flush=0
HDF Compression= 1
HDF Chunk Size= 1
HDF Spatial Parts= 1
HDF Use Max Rows=0
HDF Fixed Rows= 1
Calibration Method= 0
Calibration Iterations= 20
Calibration Max Change=0.05
Calibration Tolerance=0.2
Calibration Maximum=1.5
Calibration Minimum=0.5
Calibration Optimization Method= 1
WQ AD Non Conservative
WQ ULTIMATE=-1
WQ Max Comp Step=1HOUR
WQ Output Interval=15MIN
WQ Output Selected Increments= 0
WQ Create Restart=0
WQ Fixed Restart=0
WQ System Summary=0
WQ Write To DSS=0
Sorting and Armoring Iterations= 10
XS Update Threshold= 0.02
Bed Roughness Predictor= 0
Processes Affected by Predictor=Sediment Only
Hydraulics Update Threshold= 0.02
Energy Slope Method= 1
Volume Change Method= 1
Sediment Retention Method= 0
Sediment TS Multiplier= 1
Warm Up Method= 0
XS Weighting Method= 0
Number of US Weighted Cross Sections= 1
Number of DS Weighted Cross Sections= 1
Upstream XS Weight=0
Main XS Weight=1
Downstream XS Weight=0
Number of DS XS's Weighted with US Boundary= 1
Upstream Boundary Weight= 1
Weight of XSs Associated with US Boundary= 0
Number of US XS's Weighted with DS Boundary= 1
Downstream Boundary Weight= 0.5
Weight of XSs Associated with DS Boundary= 0.5
Percentile Method= 0
Sediment Output Level= 3
Mass or Volume Output= 0
Output Increment Type= 1
Profile and TS Output Increment= 1
Transport Output Increment 1
XS Output Flag= 0
XS Output Increment= 10
Read HDF5 Sediment Hotstart= 0
Sediment Hotstart Type= 0
Write Gradation File= 0
Read Gradation Hotstart= 0
Write HDF5 File= 1
Write Binary Output= 1
Write DSS Sediment File= 0
DSS Sediment Output Type= 1
SV Curve= 0
Specific Gage Flag= 0
Subcell Erosion Methods= 0
Subcell Deposition Methods= 0
Advection Scheme= 1
Matrix Solver= 0
Implicit Weighting Factor= 1
Maximum Outer Loop Convergence Iterations= 5
Convergence Maximum Absolute= 0.001
Convergence RMSE= 0.0001
Grain Fractions Max Abs Error= 0.001
Max Subgrid Regions= 1
Max Subgrid Length Scale= 3.402823E+38
Initial Layer Thickness= 3
Min Layer Thickness= 0.1
Max Layer Thickness= 6
Number of Layers= 5

--- WhtstneCrk.f01 (steady flow) ---

Flow Title=Flow
Program Version=6.60
Number of Profiles= 1
Profile Names=P100yr
River Rch & RM=WhtstneCrk,Main,31765
    2160
River Rch & RM=WhtstneCrk,Main,21928
    2410
River Rch & RM=WhtstneCrk,Main,18606
    2990
River Rch & RM=WhtstneCrk,Main,10500
    3380
Boundary for River Rch & Prof#=WhtstneCrk,Main            , 1
Up Type= 0
Dn Type= 3
Dn Slope=0.019474
DSS Import GetInterval= 0
DSS Import GetPeak= 0
DSS Import FillOption= 0

--- WhtstneCrk.g01 (geometry) ---

Geom Title=Geometry
Program Version=6.60

River Reach=WhtstneCrk      ,Main
Reach XY= 30
1622444.20853933447123.571839367     1621808.819      447946.384
     1622272.051      448653.203     1621950.841        449577.3
     1622024.104      450417.317     1622356.706      450697.913
     1621900.738      451415.124     1622038.617      453416.785
     1622351.868      454250.105     1623031.586      454536.748
     1623002.937       455634.94     1623607.668       456339.83
1623163.59424439457174.5992153741623365.64667741 457481.34157662
     1622787.222      457863.645     1623231.779      458578.087
     1622815.071      459686.632     1623291.621      461688.302
     1622401.082      462203.574     1622225.824      462701.531
     1621696.339       462775.61     1620918.654      464254.783
     1619293.639      465884.322     1618975.886      466666.909
     1618534.411      466726.758     1617991.225      467402.637
     1617925.234      468871.303       1618271.6         469738.
      1617286.03      470517.987     1617394.621      472276.912

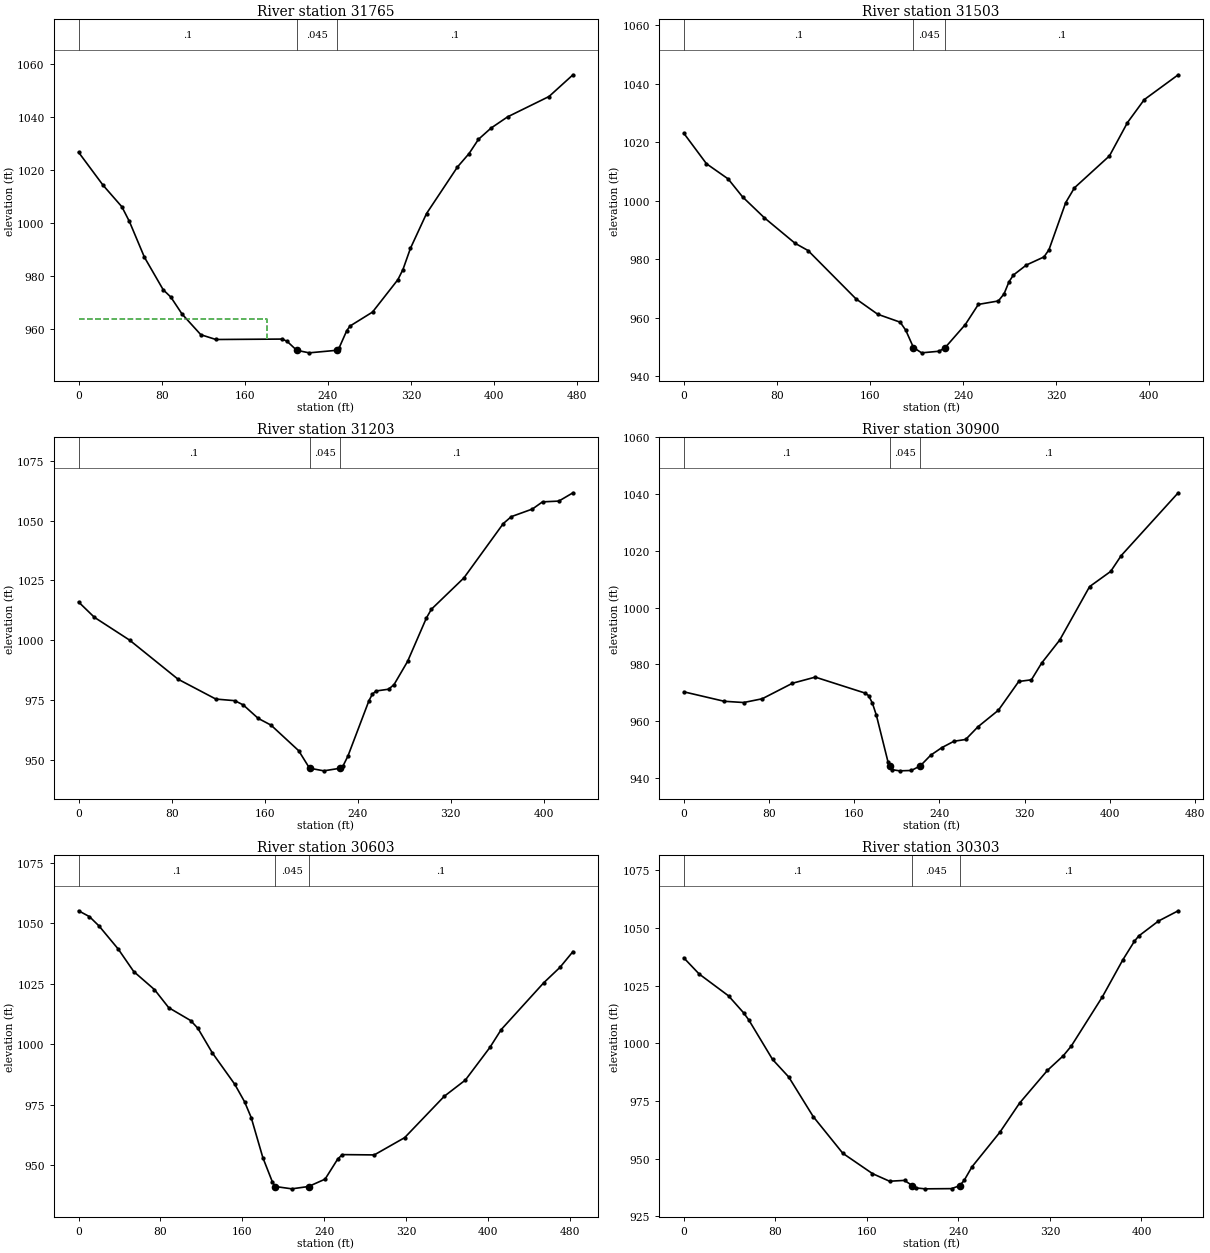
Type RM Length L Ch R = 1 ,31765   ,263.6,262.4,253
XS GIS Cut Line= 4
1622228.86096836447043.9564961531622364.55188549447107.357203646
1622446.59037166447186.6171536261622633.74783347447286.443630524
#Sta/Elev= 30
       0 1026.68    23.6 1014.26    41.7 1006.16    48.9 1000.66    63.4  987.18
    81.5  974.93    88.8   972.2    99.6  965.82   117.7  958.03   132.2  956.23
   196.1  956.39   200.7  955.56  210.05952.1608     222  951.21  248.33952.1607
   250.8  953.04   258.2  959.56   261.4  961.31     283  966.55   307.4  978.73
   312.3  982.56   319.5  990.53     335 1003.62   364.8 1021.15   375.9 1026.17
     385 1031.55   397.1 1035.77   413.1 1040.01   452.9 1047.65     476 1055.83
#Mann= 3 ,-1,0
       0      .1       0  210.05    .045       0  248.33      .1       0
#XS Ineff= 2 , 0
          181.23  963.97
Permanent Ineff=
       F       F
Bank Sta=210.05,248.33
XS Rating Curve= 0 ,0
Exp/Cntr=0.3,0.1

Type RM Length L Ch R = 1 ,31503   ,295.5,300,303.7
XS GIS Cut Line= 6
1622104.36556743447275.7655232551622180.83523075447318.293325335
1622246.38037525447354.7463364151622333.77455743447403.349913761
   1622399.32003447439.8025967631622475.78936526447482.330726922
#Sta/Elev= 30
       0 1023.02    19.5 1012.59    38.1 1007.41    50.5 1001.27    69.3   994.1
    95.6  985.41   106.8  982.92   148.1  966.36   166.7  961.13     186  958.42
   190.8  955.67  197.41949.7655   204.4  947.94   219.5  948.49  224.73949.7632
     242  957.62   253.2   964.5   270.4  965.68   275.3  968.11   279.5   972.2
   283.3  974.53   294.5  977.97   309.6  980.73   313.9  983.19   328.3  999.32
   335.8 1004.36   365.9 1015.28   381.4 1026.68   395.8 1034.51     425 1043.01
#Mann= 3 ,-1,0
       0      .1       0  197.41    .045       0  224.73      .1       0
Bank Sta=197.41,224.73
XS Rating Curve= 0 ,0
Exp/Cntr(USF)=0,0
Exp/Cntr=0.3,0.1

Type RM Length L Ch R = 1 ,31203   ,309.4,302.4,299.1
XS GIS Cut Line= 6
1621952.40491334447454.7740235031622012.76798159447518.118713096
1622064.50803559447572.4142081741622133.49444617447644.807764173
1622185.23450017447699.1032592511622245.59756842447762.447620749
#Sta/Elev= 30
       0 1016.03    13.6 1009.63    43.8 1000.14    85.5  983.83     118  975.54
   134.3  974.87   141.6  973.08   154.4  967.49   165.4  964.68   189.2  954.01
  198.54946.7131   210.8  945.61  225.12946.7134   227.1  947.45   231.5  951.72
   249.6  974.86   252.6  977.63   255.8  978.92   266.5  979.65   271.2   981.6
   282.8  991.23     299 1009.36   303.3 1013.01   331.2 1026.05   365.1 1048.74
     372 1051.62   390.1 1054.79   398.8 1057.78   412.8  1058.1     425 1061.57
#Mann= 3 ,-1,0
       0      .1       0  198.54    .045       0  225.12      .1       0
Bank Sta=198.54,225.12
XS Rating Curve= 0 ,0
Exp/Cntr(USF)=0,0
Exp/Cntr=0.3,0.1

Type RM Length L Ch R = 1 ,30900   ,323.8,297.6,280.6
XS GIS Cut Line= 6
1621673.94484034447715.3095916661621754.55425918447749.344300509
 1621823.6482811447778.5168143361621913.87185392 447821.91764617
1621978.50787951447861.6478816721622103.19759075447876.583547339
#Sta/Elev= 30
       0  970.36    37.9  967.03    56.2  966.59    73.6  967.91     102  973.38
   123.4  975.54   169.9  969.95   173.5  969.03   177.1   966.3   180.8  962.06
   191.7  945.65  193.42944.2614   195.8  942.92   202.6  942.53   213.6  942.66
  221.94944.2645   231.8  948.05   242.2   950.7   253.6  952.95   264.6  953.58
   276.2  958.07   295.3  963.87   314.4     974   326.3  974.59   335.8  980.43
   352.9  988.61   380.9 1007.41   400.7 1012.76   410.6 1018.34   464.1 1040.46
#Mann= 3 ,-1,0
       0      .1       0  193.42    .045       0  221.94      .1       0
Bank Sta=193.42,221.94
XS Rating Curve= 0 ,0
Exp/Cntr(USF)=0,0
Exp/Cntr=0.3,0.1

Type RM Length L Ch R = 1 ,30603   ,285.9,300,313.3
XS GIS Cut Line= 6
1621750.00472759448235.9473299241621800.40062417448164.417289257
1621843.59673201448103.1060601771621901.19176118448021.357536003
1621968.89142892447969.1279816781622098.38952951447930.323597342
#Sta/Elev= 30
       0 1055.06    10.6 1052.65      20 1048.79    38.8 1039.23    53.9 1029.96
    74.2  1022.5    88.1 1015.04   109.5 1009.73   116.6 1006.52   130.7  996.38
   152.6  983.43   162.2   976.2   168.7  969.67   180.1  953.09   189.5  942.97
   192.3  941.17   208.4  940.21  224.71  941.17   240.9  944.21   253.3  952.54
   257.8  954.35     289  954.22   318.7  961.36   357.4  978.44     378  985.13
     402  998.62   413.1 1006.02   454.6 1025.32   470.5  1031.7   483.2 1038.22
#Mann= 3 ,-1,0
       0      .1       0   192.3    .045       0  224.71      .1       0
Bank Sta=192.3,224.71
XS Rating Curve= 0 ,0
Exp/Cntr(USF)=0,0
Exp/Cntr=0.3,0.1

Type RM Length L Ch R = 1 ,30303   ,301.1,300,299
XS GIS Cut Line= 6
 1621924.9905981448328.5796905911621996.87431259448268.391490757
1622064.12942742448233.2826370891622158.74209909448200.902780592
1622229.70160285448176.6177241651622312.48752651448148.285103679
#Sta/Elev= 30
       0 1037.09    13.4  1030.1    39.1 1020.62    52.2 1013.31    56.8 1010.18
    77.6  993.04    91.7  985.45   113.1  968.29     139  952.37   164.9  943.57
   179.8  940.27   192.9  940.63  199.77938.3277   203.3  937.35   210.8  936.97
     234  937.06  241.04 938.326     245  940.62   251.9  946.54   276.2  961.48
   293.5  974.16   317.8  988.32   331.6  994.63   338.6  998.83   365.8 1020.18
   383.7 1036.23   393.7  1044.2   397.5 1046.53   414.8 1053.04   432.1  1057.5
#Mann= 3 ,-1,0
       0      .1       0  199.77    .045       0  241.04      .1       0
Bank Sta=199.77,241.04
XS Rating Curve= 0 ,0
Exp/Cntr(USF)=0,0
Exp/Cntr=0.3,0.1

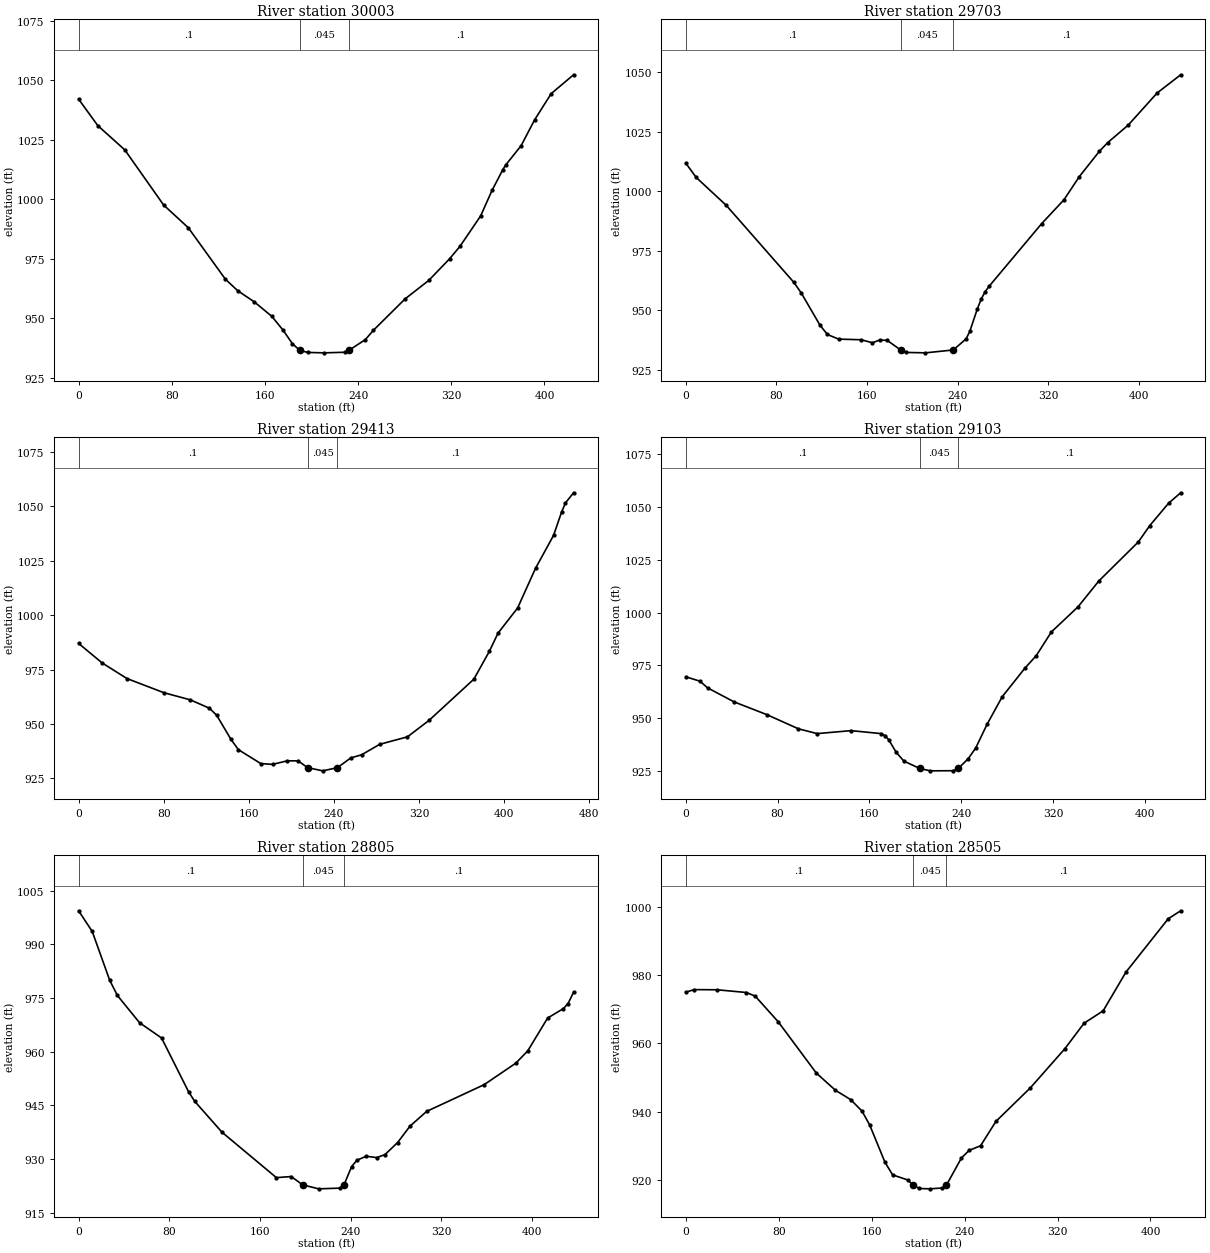
Type RM Length L Ch R = 1 ,30003   ,287.7,300,310.3
XS GIS Cut Line= 6
1622018.36344284448577.1845083391622099.61065568448544.701305583
1622169.25126442448516.8588415831622262.10508133 448479.73555626
1622331.74536201448451.8927641661622412.27374426448417.611336678
#Sta/Elev= 30
       0 1042.05    16.5 1030.92    39.7 1020.71      73  997.56    94.2     988
     126   966.4   136.6  961.55   150.8  956.87   165.9  950.77   175.5  944.99
   183.5  939.34  189.84936.4833   196.7   935.6   210.8  935.43   228.5  935.67
   232.1 936.482   246.2  940.99   253.2  944.94   280.4  958.13   300.8  965.92
   318.5  974.94   327.4  980.14   345.2  992.97     355  1003.7   364.2 1012.36
   366.6  1014.3     380 1022.51   391.5 1033.31   405.8 1044.37     425 1052.29
#Mann= 3 ,-1,0
       0      .1       0  189.84    .045       0   232.1      .1       0
Bank Sta=189.84,232.1
XS Rating Curve= 0 ,0
Exp/Cntr(USF)=0,0
Exp/Cntr=0.3,0.1

Type RM Length L Ch R = 1 ,29703   ,261.4,290,303
XS GIS Cut Line= 5
1622050.74625209448759.9859800041622137.55218084448770.985301837
1622211.95721576448780.4134325831622311.16403835448792.984273583
1622474.06411057448731.474048624
#Sta/Elev= 30
       0 1011.81     9.3 1005.73    35.7  994.06    95.3  961.71   101.9  957.21
   118.4  943.68     125  939.73   134.9  937.79   154.8  937.52   164.7  936.25
   171.3  937.46   177.9  937.21  189.57933.2255   194.5  932.19   211.5  932.02
  236.04933.2272   247.4  937.91   250.7  941.18   257.3  950.57   260.6  954.54
     264   957.6   267.5  959.93     314  986.34   333.6  996.33   347.1 1006.03
   364.9 1016.75   372.2 1020.37   390.4 1027.79   415.8 1041.24   436.6 1048.91
#Mann= 3 ,-1,0
       0      .1       0  189.57    .045       0  236.04      .1       0
Bank Sta=189.57,236.04
XS Rating Curve= 0 ,0
Exp/Cntr(USF)=0,0
Exp/Cntr=0.3,0.1

Type RM Length L Ch R = 1 ,29413   ,335.4,310,292.5
XS GIS Cut Line= 6
1622027.79616676 448853.449047671622096.29996675448921.230408177
 1622158.3223084449002.4334105361622166.93091704449069.150990231
1622236.89811076449138.2024151681622325.82542634449186.316164091
#Sta/Elev= 30
       0  987.02    22.1  978.07    45.5  970.88    80.2  964.38     105  961.11
     123  957.25   129.8     954   143.2  942.96   150.2  938.22   171.3  931.82
   182.4  931.49   195.9  933.08   206.3  933.11  215.22929.9675   229.5  928.51
  243.27929.9664   255.9  934.47   265.9  935.86     283  940.69   309.1  944.13
   329.4  951.69   371.5  970.61     386  983.33   394.2  991.74   412.6 1003.28
   429.5 1021.56   446.4 1036.63   453.9 1047.28   457.6 1051.56   465.2 1056.19
#Mann= 3 ,-1,0
       0      .1       0  215.22    .045       0  243.27      .1       0
Bank Sta=215.22,243.27
XS Rating Curve= 0 ,0
Exp/Cntr(USF)=0,0
Exp/Cntr=0.3,0.1

Type RM Length L Ch R = 1 ,29103   ,283.9,298.1,313.9
XS GIS Cut Line= 6
1621899.92896843449281.9107891771621993.02983209 449290.28085117
 1622068.1139995449287.9317745121622167.72698925449279.142422006
1622242.43681359449272.5505716651622329.59805658449264.859970257
#Sta/Elev= 30
       0  969.66    12.4  967.59      19  964.45    42.1  957.82      71  951.71
    98.1  945.11   114.5  942.83     144  944.23   170.3  942.83   173.6  941.86
   176.9  939.85   183.4  933.95     190  929.87  203.85926.3565   213.1  925.25
   232.9  925.31  237.39 926.358     246  930.93   252.6  936.03   262.5  947.25
   275.7  960.26   295.4   973.7   305.3  979.63   318.5  990.83   341.7 1002.69
   359.8 1014.88   394.2 1033.31   404.1 1040.98   420.6 1051.62   431.1 1056.54
#Mann= 3 ,-1,0
       0      .1       0  203.85    .045       0  237.39      .1       0
Bank Sta=203.85,237.39
XS Rating Curve= 0 ,0
Exp/Cntr(USF)=0,0
Exp/Cntr=0.3,0.1

Type RM Length L Ch R = 1 ,28805   ,311.4,299.4,279.6
XS GIS Cut Line= 6
1621836.48093259449378.6258188341621895.72031543449443.022343591
1621946.49711676449498.2194116711622016.92414126449569.309164509
 1622088.1612035449605.5026616751622176.62657775449638.008174092
#Sta/Elev= 30
       0  999.34      12  993.58    27.4  979.96    34.2  975.69    53.8  968.06
    73.2   963.8      97   948.8   102.3  946.16   126.5  937.48   174.5  924.79
   187.6   925.1   197.6922.7844   211.8  921.66   230.5  921.86  234.19922.7874
   240.9   927.9   245.6  929.66   253.8  930.76     263  930.39   270.3  931.22
   281.4  934.57   292.4  939.18   307.1   943.3   357.8  950.76   385.8  956.78
   396.3  960.22   413.8  969.37   427.8  972.03   431.8  973.41   436.7  976.56
#Mann= 3 ,-1,0
       0      .1       0   197.6    .045       0  234.19      .1       0
Bank Sta=197.6,234.19
XS Rating Curve= 0 ,0
Exp/Cntr(USF)=0,0
Exp/Cntr=0.3,0.1

Type RM Length L Ch R = 1 ,28505   ,339.3,338.3,337
XS GIS Cut Line= 6
1621770.38067108449827.0766935941621858.38705675449825.335227251
1621933.79438625449823.6357555841622033.58814992 449815.58983992
1622108.23104526449808.4244999291622195.28566118449799.938296422
#Sta/Elev= 30
       0  974.97     7.3  975.73    27.1  975.68    52.3  974.88    59.9   973.8
    79.6  966.31   112.4  951.28   128.8  946.24     142  943.48   151.8  940.09
   158.4  936.01   171.5  925.12   178.1  921.42   191.3  919.91  195.52918.4498
   201.1  917.43   210.4  917.33   220.9  917.59  224.45918.4503   237.3  926.36
   243.9   928.6   253.8  929.96     267   937.1   296.6  946.92   326.3  958.39
   342.8  965.86   359.3  969.52     379  980.91   415.3   996.5     426  998.84
#Mann= 3 ,-1,0
       0      .1       0  195.52    .045       0  224.45      .1       0
Bank Sta=195.52,224.45
XS Rating Curve= 0 ,0
Exp/Cntr(USF)=0,0
Exp/Cntr=0.3,0.1

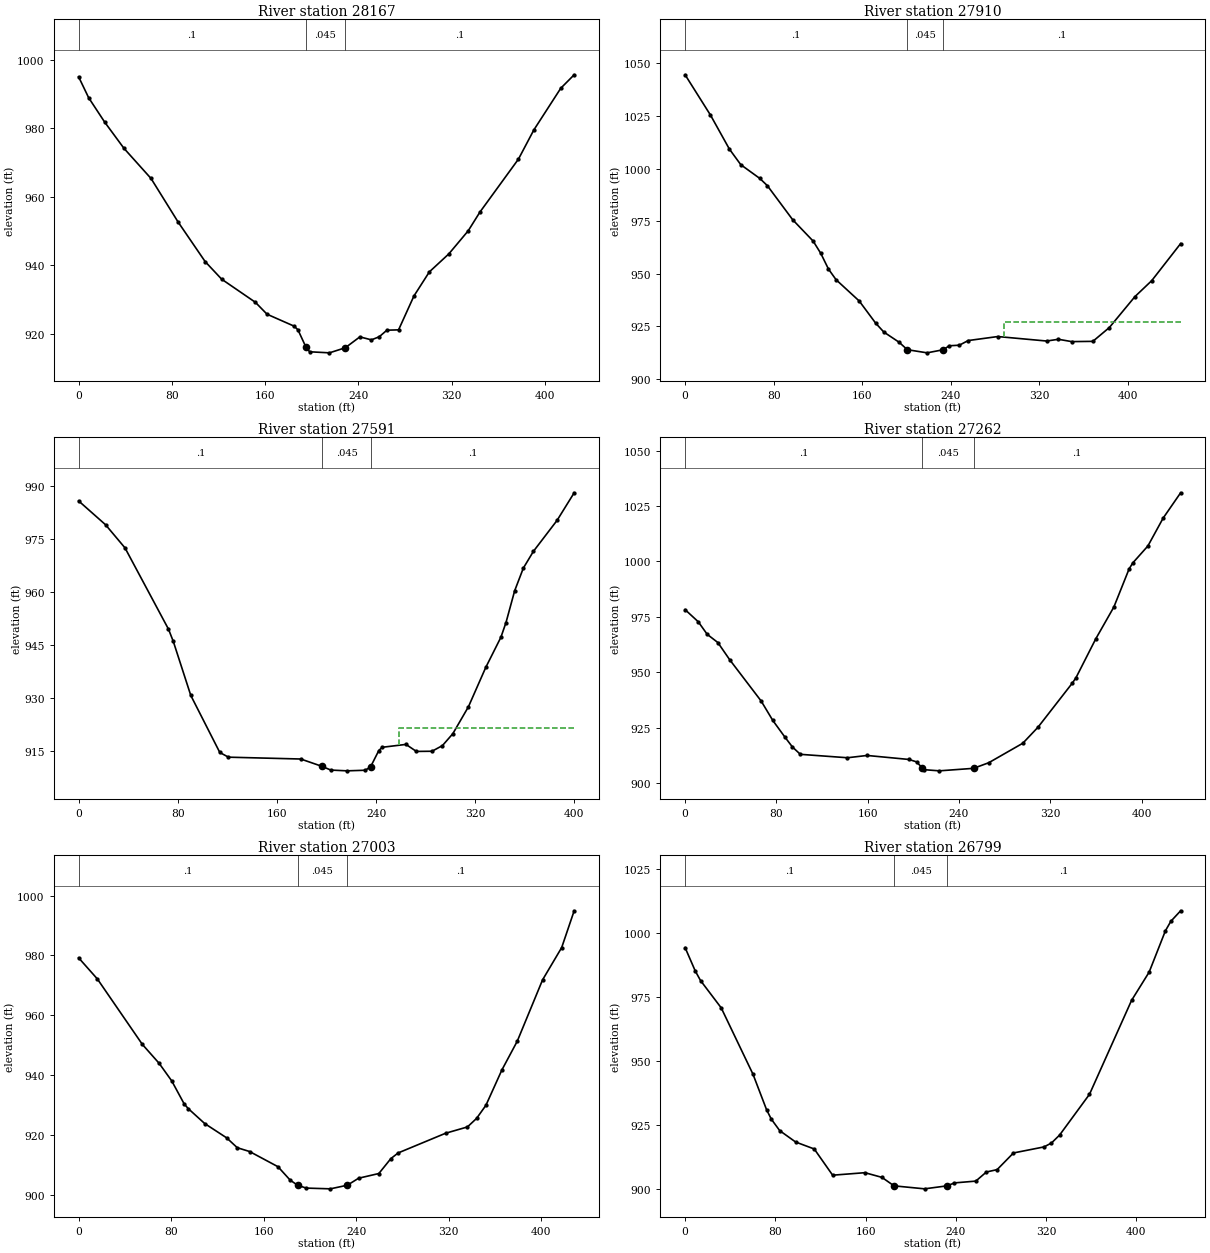
Type RM Length L Ch R = 1 ,28167   ,260.6,257.5,251.1
XS GIS Cut Line= 6
 1621785.2920983450186.302054237 1621871.8411378450173.436594408
 1621946.0260288450162.4090574051622044.93921679450147.705674749
1622119.12410779450136.6781377461622205.67314729450123.813005995
#Sta/Elev= 30
       0  995.03     8.6  988.94    22.3  981.84    38.9  974.16    62.1  965.37
    85.3  952.67   108.5  941.12   122.7  935.97   151.6  929.23   161.6  925.75
   184.8  922.27   188.1   921.2   194.7  916.33   198.1  914.79   215.1  914.48
   228.7  915.96   241.2  919.14   251.1  918.27   257.8  919.17   264.4  921.09
   274.4  921.19   287.6  931.09   300.8  938.11   317.5  943.36   334.1  950.09
   344.2  955.58   377.2  971.02   390.4  979.53   413.5  991.71     425  995.64
#Mann= 3 ,-1,0
       0      .1       0   194.7    .045       0   228.7      .1       0
Bank Sta=194.7,228.7
XS Rating Curve= 0 ,0
Exp/Cntr(USF)=0,0
Exp/Cntr=0.3,0.1

Type RM Length L Ch R = 1 ,27910   ,316.8,318.8,311
XS GIS Cut Line= 6
1621821.50360034450481.018955261 1621905.2088135450455.628258005
1621976.45112509450432.230338916 1622069.8069095450387.663498923
 1622142.3776305450345.7183728371622226.74655625450296.139731839
#Sta/Elev= 30
       0 1044.62    22.9 1025.47      40 1009.29    50.3 1001.86    67.5  995.32
    74.3  991.89    97.2  975.67   115.7   965.5   122.6  959.65   129.5  952.22
   136.4  947.14   157.3  937.02   172.1  926.52   179.5  922.27   193.2  917.46
  200.74913.8748   218.6  912.38  233.36 913.876   238.5  915.74   247.7  916.01
   255.7  918.22   282.4  920.13   326.5     918   337.2  918.82   349.2  917.72
   368.3  917.84   383.2  924.41   406.3  939.11   421.5  946.72   447.6  964.34
#Mann= 3 ,-1,0
       0      .1       0  200.74    .045       0  233.36      .1       0
#XS Ineff= 2 , 0
                          287.73          927.26
Permanent Ineff=
       F       F
Bank Sta=200.74,233.36
XS Rating Curve= 0 ,0
Exp/Cntr(USF)=0,0
Exp/Cntr=0.3,0.1

Type RM Length L Ch R = 1 ,27591   ,305.1,328.7,340.2
XS GIS Cut Line= 4
1622103.98269418450721.2478055061622184.60851717450669.199025095
1622309.56672511450567.3084819131622398.75048753450455.994210556
#Sta/Elev= 30
       0   985.9    21.7  979.16    37.4   972.6    72.5  949.57    76.4  946.08
    90.5  930.79   113.9  914.64   120.9  913.31   179.2  912.79  196.67910.6716
   203.4  909.66   216.5  909.44   231.4  909.61  235.68910.6692   242.2   915.2
   244.9  916.11   264.1  916.93   272.5  914.94   285.1  914.99   293.5  916.59
   301.9  919.96   314.5   927.6   328.5  938.76   340.7  947.29   344.8  951.46
   351.8  960.46   358.8  966.88   366.9  971.61     386  980.39   399.8  988.21
#Mann= 3 ,-1,0
       0      .1       0  196.67    .045       0  235.68      .1       0
#XS Ineff= 2 , 0
                          258.77          921.65
Permanent Ineff=
       F       F
Bank Sta=196.67,235.68
XS Rating Curve= 0 ,0
Exp/Cntr(USF)=0,0
Exp/Cntr=0.3,0.1

Type RM Length L Ch R = 1 ,27262   ,228.7,259.2,276.4
XS GIS Cut Line= 3
1622088.34608525 450824.202644981622245.55394109450873.983217076
1622511.33178719450917.819574693
#Sta/Elev= 30
       0  978.28    11.5  972.84    19.4  967.15    28.7  963.46      39  955.77
    66.6  937.14    76.9  928.32    87.2  921.03    94.1  916.36     101  913.07
   142.3  911.53   159.5  912.56   196.2  910.76   202.9  909.66  207.99  906.84
   209.5  906.15   222.8  905.63   252.8  906.76   266.1  909.28     296  918.08
   309.3   925.3   339.2  945.06   342.5  947.52   359.9  965.11   375.8  979.49
   389.1  996.61   392.4  999.37   405.6 1006.98     419 1019.57   434.3 1030.96
#Mann= 3 ,-1,0
       0      .1       0  207.99    .045       0   252.8      .1       0
Bank Sta=207.99,252.8
XS Rating Curve= 0 ,0
Exp/Cntr(USF)=0,0
Exp/Cntr=0.3,0.1

Type RM Length L Ch R = 1 ,27003   ,218.4,203.9,187.5
XS GIS Cut Line= 6
1622055.44309309450856.595303833 1622092.9548291450936.102034584
 1622120.8169781 451005.788246931622154.54460092451099.928806677
1622179.84015401451170.5343085081622233.38433826451243.521695346
#Sta/Elev= 30
       0  979.18    16.2  972.12    55.1  950.25    69.6  943.93    80.5  938.05
    91.3  930.33    94.8  928.78     109   923.8     128  919.01   137.2  915.71
   147.8  914.45   172.4  909.36   182.9  904.89  189.31903.1849   196.8  902.22
   217.7  901.97  232.37903.1851   242.1  905.52   259.6  907.09     270  912.08
   276.3  913.97   317.3  920.55   336.2  922.66   344.1  925.51   352.2   929.9
     366  941.71   379.3  951.33   401.2  971.84   417.7  982.61   428.5  994.91
#Mann= 3 ,-1,0
       0      .1       0  189.31    .045       0  232.37      .1       0
Bank Sta=189.31,232.37
XS Rating Curve= 0 ,0
Exp/Cntr(USF)=0,0
Exp/Cntr=0.3,0.1

Type RM Length L Ch R = 1 ,26799   ,269.5,250.7,229.7
XS GIS Cut Line= 3
1621831.05868553451066.9315315391621956.28355472451161.905238626
1622201.17860963451302.059223547
#Sta/Elev= 30
       0  994.14       9  985.02    13.7  981.26      32  970.61    60.2  944.66
    72.2  930.83    76.4  927.14    83.9  922.62      98  918.18   114.5  915.46
   130.8  905.22   159.4   906.2   174.5  904.37  185.22 901.058   212.3  899.89
  232.21 901.058   238.8  902.21   257.7  902.91   267.1  906.47   276.6  907.39
   291.1  913.91   318.2  916.27   324.8   917.8     332   920.9   358.5  936.83
   395.8  973.52   411.4  984.58   425.8 1000.71   430.6 1004.41   439.3 1008.53
#Mann= 3 ,-1,0
       0      .1       0  185.22    .045       0  232.21      .1       0
Bank Sta=185.22,232.21
XS Rating Curve= 0 ,0
Exp/Cntr(USF)=0,0
Exp/Cntr=0.3,0.1

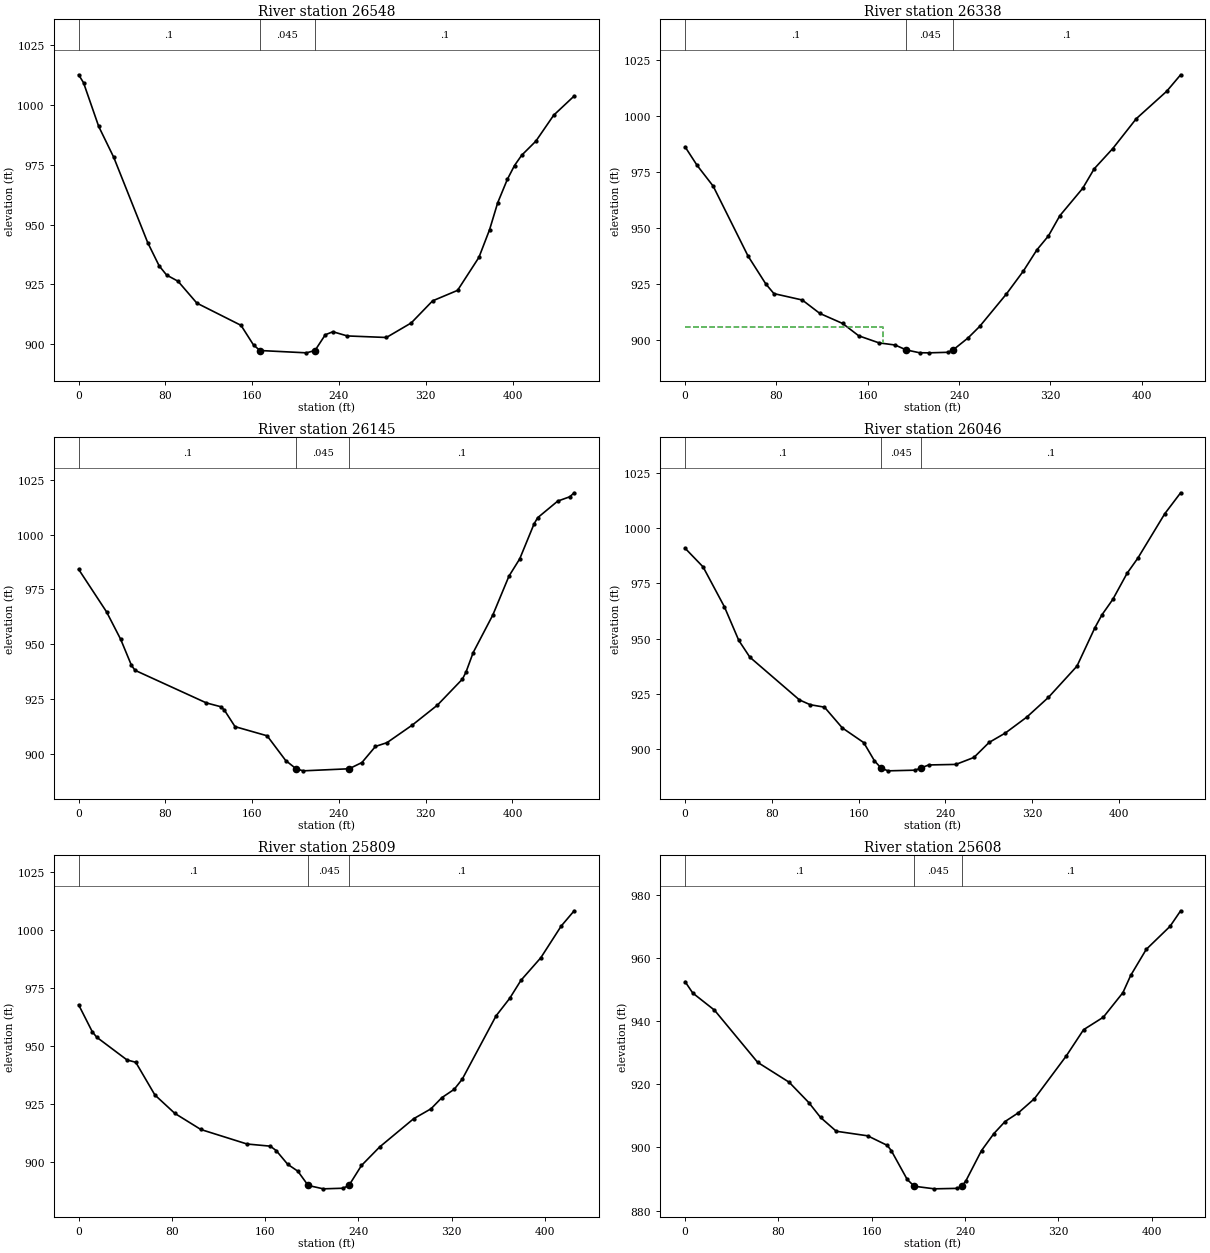
Type RM Length L Ch R = 1 ,26548   ,207.8,210.3,206.6
XS GIS Cut Line= 3
1621721.04172049451473.9724018841621943.08085574451394.876915938
1622164.16703332451392.018042952
#Sta/Elev= 30
       0 1012.56     4.5 1009.26    18.5  990.99    32.4  978.05    63.7  942.45
    74.2  932.79    81.1  928.93    91.6  926.35     109   917.2   149.7  907.92
   161.2  899.73  167.14897.4127     210  896.44  217.89897.4159   227.4     904
   234.4  905.25   247.6   903.5   283.7  902.85   306.6  908.93   326.3  918.15
   349.3  922.53     369  936.31   378.8  947.85   386.3  959.11   395.2  968.89
   401.8  974.67   408.4  978.95   421.5  984.85   437.9  995.67   456.8  1003.7
#Mann= 3 ,-1,0
       0      .1       0  167.14    .045       0  217.89      .1       0
Bank Sta=167.14,217.89
XS Rating Curve= 0 ,0
Exp/Cntr(USF)=0,0
Exp/Cntr=0.3,0.1

Type RM Length L Ch R = 1 ,26338   ,201.3,193,183.6
XS GIS Cut Line= 3
1621814.01972352  451660.77322161622046.20993392451566.371176791
1622226.11760457451530.861220106
#Sta/Elev= 30
       0  986.08    10.5  977.83    24.6  968.55    55.1   937.4    70.7  924.92
    77.8  920.62   102.6  917.77     118  911.78     138  907.29   152.1  901.79
   169.8  898.65     184  897.68  193.65 895.506   205.3  894.24   213.7   894.2
   230.1  894.44  234.72895.5057   247.8  900.84     258  905.99   281.4  920.45
   296.3  930.71   308.1  940.13   318.2  946.35   328.2  955.37   348.2  967.57
   358.3  976.29   374.5  985.29   395.1  998.62   421.8 1010.88     434 1018.23
#Mann= 3 ,-1,0
       0      .1       0  193.65    .045       0  234.72      .1       0
#XS Ineff= 2 , 0
          173.65  905.61
Permanent Ineff=
       F       F
Bank Sta=193.65,234.72
XS Rating Curve= 0 ,0
Exp/Cntr(USF)=0,0
Exp/Cntr=0.3,0.1

Type RM Length L Ch R = 1 ,26145   ,92.7,99,103.2
XS GIS Cut Line= 5
1621830.96481397 451810.565979391622004.92532297451796.260240162
1622099.15339874451722.2191008931622173.73494248451730.129518151
1622260.74690756451739.357846141
#Sta/Elev= 30
       0  984.15    25.7  964.75    38.8  952.14    48.7  940.28      52  938.01
   117.8  923.11     131  921.38   134.3  919.89   144.2  912.27   173.8  908.09
   190.9   896.8  200.51893.0264     207  892.08  249.41893.0265   261.2  895.88
   273.7  903.24   284.3  904.95   307.7  913.01   330.8   922.1   353.9  934.01
   357.2  937.25   363.8  946.14   381.9  963.29   396.8  981.06   406.7  988.94
   419.9 1004.88   423.2 1007.71   441.7 1015.31   452.9 1017.31   456.9 1019.12
#Mann= 3 ,-1,0
       0      .1       0  200.51    .045       0  249.41      .1       0
Bank Sta=200.51,249.41
XS Rating Curve= 0 ,0
Exp/Cntr(USF)=0,0
Exp/Cntr=0.3,0.1

Type RM Length L Ch R = 1 ,26046   ,231.9,236.9,239.3
XS GIS Cut Line= 5
  1621830.190118451889.3950178311622004.15062699451875.089278603
1622098.37870276451801.048139334 1622172.9602465451808.958556592
1622259.97221158451818.186884582
#Sta/Elev= 30
       0  990.88    16.6  982.42    36.3  964.32    49.5  949.17    59.7  941.58
   105.4  922.25   115.3  920.07   128.5  918.96   144.9  909.59   164.7  902.92
   174.6  894.68  180.72 891.379   187.1  890.14   212.1  890.44  217.16891.3789
   224.6   892.8   249.7  893.05   266.3   896.2   280.3  902.99   295.3  907.26
   315.1  914.48     335  923.39   361.3  937.51   377.8  954.86   384.4  960.79
   394.3  967.69   407.5  979.52   417.4  986.37   442.3 1006.52   456.9 1015.98
#Mann= 3 ,-1,0
       0      .1       0  180.72    .045       0  217.16      .1       0
Bank Sta=180.72,217.16
XS Rating Curve= 0 ,0
Exp/Cntr(USF)=0,0
Exp/Cntr=0.3,0.1

Type RM Length L Ch R = 1 ,25809   ,193.7,200.8,204.5
XS GIS Cut Line= 6
1621888.84237643452184.0824782551621965.93572618452142.695750013
 1622032.0156465452107.221083418 1622120.1220976 452059.92196542
1622186.20201792 452024.447298841622263.29536767451983.060570583
#Sta/Elev= 30
       0  967.67    11.7  956.08    15.5  953.72    41.5  943.92      49  942.92
    65.4  928.84    82.5  920.91   104.8  913.97   144.4  907.72   164.4  906.79
   169.5  904.86   179.3  898.98     188  896.01  196.84 889.881   209.8  888.41
   226.7  888.67  231.85889.8833   242.6  898.48   258.2  906.46   287.3   918.6
   302.2  922.88   311.5  927.68   322.1  931.27     329  935.64     358   962.9
   369.7  970.45   379.4  978.25   396.4  987.95   413.9 1001.61     425 1008.17
#Mann= 3 ,-1,0
       0      .1       0  196.84    .045       0  231.85      .1       0
Bank Sta=196.84,231.85
XS Rating Curve= 0 ,0
Exp/Cntr(USF)=0,0
Exp/Cntr=0.3,0.1

Type RM Length L Ch R = 1 ,25608   ,139,143.2,145.5
XS GIS Cut Line= 2
1621950.07461202452310.3585649211622364.11946883452215.183824344
#Sta/Elev= 30
       0   952.6     6.6  948.98    25.2  943.56    62.2  927.01    89.2   920.7
     106  914.26   116.1  909.53   129.6  905.15   156.5   903.7   173.3  900.67
   176.7  899.04   190.4  889.86  196.41 887.709   213.7  886.88   233.2  887.03
   237.2  887.71   240.7  889.41   254.1  899.02   264.7  904.41   274.3  908.24
   285.8  911.03   299.5  915.49   326.8  929.06   341.6  937.37   358.5  941.32
   375.3  949.11     382  954.59   395.3  962.84   415.7  970.15   424.8  975.09
#Mann= 3 ,-1,0
       0      .1       0  196.41    .045       0   237.2      .1       0
Bank Sta=196.41,237.2
XS Rating Curve= 0 ,0
Exp/Cntr(USF)=0,0
Exp/Cntr=0.3,0.1

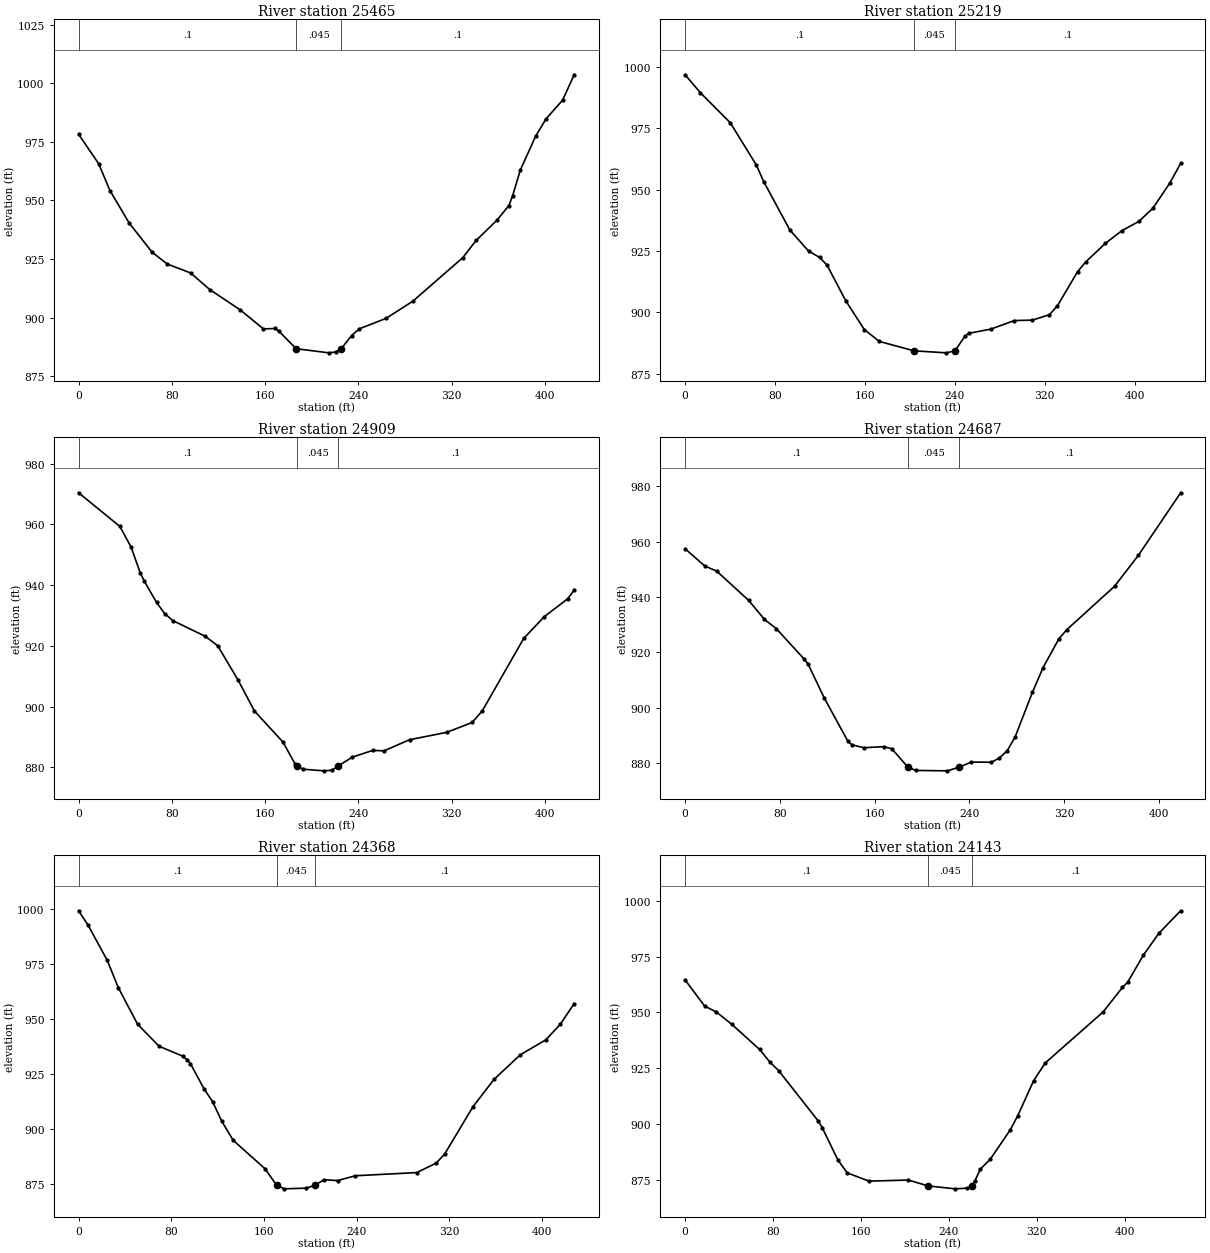
Type RM Length L Ch R = 1 ,25465   ,242.5,245.8,250.1
XS GIS Cut Line= 6
1621967.45451571452417.1999640491622054.75552221  452411.3013538
1622129.58476888452406.2455896311622229.35720712452399.504133302
1622304.18645379452394.4483691331622391.48778838452388.549758884
#Sta/Elev= 30
       0  978.26    17.1  965.79    26.9  954.22    43.4  940.33    63.1  927.87
      76  922.85      96  919.05   112.4  911.97   138.7  903.22   158.5  895.13
   168.3  895.31   171.6  894.24  186.57886.6725   214.6  884.91   220.8   885.3
  225.25886.6725   234.1  892.27   240.7  895.17   263.7  899.64   286.7     907
   329.5  925.59     341  932.97   358.7  941.55   368.9  947.76   372.2  951.98
   378.8  962.99   391.9  977.41     401  984.98     415   992.8     425 1003.71
#Mann= 3 ,-1,0
       0      .1       0  186.57    .045       0  225.25      .1       0
Bank Sta=186.57,225.25
XS Rating Curve= 0 ,0
Exp/Cntr(USF)=0,0
Exp/Cntr=0.3,0.1

Type RM Length L Ch R = 1 ,25219   ,306.2,310.3,313.9
XS GIS Cut Line= 3
1621964.40230597452616.3093155361622254.34173497452657.521420864
 1622390.0723178452598.378582768
#Sta/Elev= 30
       0  996.86    13.7   989.5    40.2   977.3    63.4  960.04      70  953.25
    93.2  933.57   109.8  924.99   119.7  922.37   126.3  919.24   142.9  904.74
   159.4  892.98   172.7  888.14  203.58884.3004   232.4  883.47  240.12 884.301
   248.9  890.18   252.2  891.41   272.1  893.16   292.9  896.63     309  896.82
   324.2  899.02   331.3  902.68   349.2  916.56   356.3  920.48   373.8  928.06
   388.6  933.28   403.7  937.04   416.2  942.43   431.2  952.64   440.9  960.71
#Mann= 3 ,-1,0
       0      .1       0  203.58    .045       0  240.12      .1       0
Bank Sta=203.58,240.12
XS Rating Curve= 0 ,0
Exp/Cntr(USF)=0,0
Exp/Cntr=0.3,0.1

Type RM Length L Ch R = 1 ,24909   ,224.6,222.1,219.7
XS GIS Cut Line= 6
1621905.41813068452873.2720447631621987.44782226452903.725067839
1622057.75903334 452929.827705921622151.50720543452964.631114006
1622221.81841651452990.7334240081622303.84810808453021.186447084
#Sta/Elev= 30
       0  970.44    35.3  959.38    44.9  952.65    52.8  944.12    56.3  941.39
    66.8  934.34    73.8  930.66    80.8  928.35   108.7  923.17   119.3  920.08
   136.9  908.68   150.8  898.59   175.3  888.36   185.8  881.04   187.7880.3723
   192.8  879.43   210.3   878.9   217.3  879.09  222.08880.3737   234.8  883.44
   252.3  885.62   261.9  885.49   283.8  889.14   315.8  891.58   337.5  894.82
   346.1  898.59   381.8  922.53   399.3  929.63   419.5  935.56     425  938.39
#Mann= 3 ,-1,0
       0      .1       0   187.7    .045       0  222.08      .1       0
Bank Sta=187.7,222.08
XS Rating Curve= 0 ,0
Exp/Cntr(USF)=0,0
Exp/Cntr=0.3,0.1

Type RM Length L Ch R = 1 ,24687   ,326.7,318.7,297.6
XS GIS Cut Line= 2
1621840.27422627453115.3751146471622248.92597319453204.636053511
#Sta/Elev= 30
       0  957.45    16.6  951.23    26.7  949.36    53.6   938.8      67   931.9
    77.1  928.51   100.6   917.5     104  915.59   117.4  903.51   137.5  887.75
   140.9  886.52     151  885.46   167.8  885.85   174.5  885.09   187.9  878.51
   194.6  877.25   221.5   877.1   231.6  878.49   241.6  880.28   258.4  880.22
   265.1  881.66   271.9  884.39   278.6  889.38   293.2  905.52   302.2  914.47
   315.5  924.85   322.2  928.18   362.5  943.88   382.7  955.13   418.3  977.72
#Mann= 3 ,-1,0
       0      .1       0   187.9    .045       0   231.6      .1       0
Bank Sta=187.9,231.6
XS Rating Curve= 0 ,0
Exp/Cntr(USF)=0,0
Exp/Cntr=0.3,0.1

Type RM Length L Ch R = 1 ,24368   ,210.8,225.2,220.6
XS GIS Cut Line= 2
 1621908.8402469453564.8727626681622273.34655261453341.023007865
#Sta/Elev= 30
       0  999.25     7.9  992.94    24.7  976.77    34.2  964.41    50.9  947.75
    69.5  937.73    89.7  933.31    93.9  931.56    96.5   929.9   108.2  918.47
   115.7  912.59   123.4  903.87   133.5  895.01   160.7  882.26  171.03  874.63
   177.4  873.03   196.6  873.35   203.7874.6215     212  877.18   223.5  876.78
   238.9  878.97   291.9  880.41   308.6  884.69   315.9  888.74   340.4  910.28
   358.6  922.71   381.4  933.93   403.1  940.58   415.7  947.63   427.8  957.13
#Mann= 3 ,-1,0
       0      .1       0  171.03    .045       0   203.7      .1       0
Bank Sta=171.03,203.7
XS Rating Curve= 0 ,0
Exp/Cntr(USF)=0,0
Exp/Cntr=0.3,0.1

Type RM Length L Ch R = 1 ,24143   ,130.2,134.1,137.3
XS GIS Cut Line= 2
1622013.98185875453681.7799484141622429.09021631453505.959259775
#Sta/Elev= 30
       0  964.58    17.8  952.85    28.5  950.18    42.4   944.7    67.7  933.42
    77.4  927.58      85  923.94   121.2  901.24   124.7  898.35     139  883.79
   147.5     878   167.3   874.3   203.1  874.79  221.24 872.132   245.9  870.84
   256.6  871.14  260.61 872.132   263.7  874.49   268.6  879.67   277.7   884.2
   295.8   897.3   302.7  903.73   317.1  919.42   327.7  927.36   380.3  950.23
   397.8   961.2   402.6  963.55   416.9  975.72   431.1  985.58   450.8  995.62
#Mann= 3 ,-1,0
       0      .1       0  221.24    .045       0  260.61      .1       0
Bank Sta=221.24,260.61
XS Rating Curve= 0 ,0
Exp/Cntr(USF)=0,0
Exp/Cntr=0.3,0.1