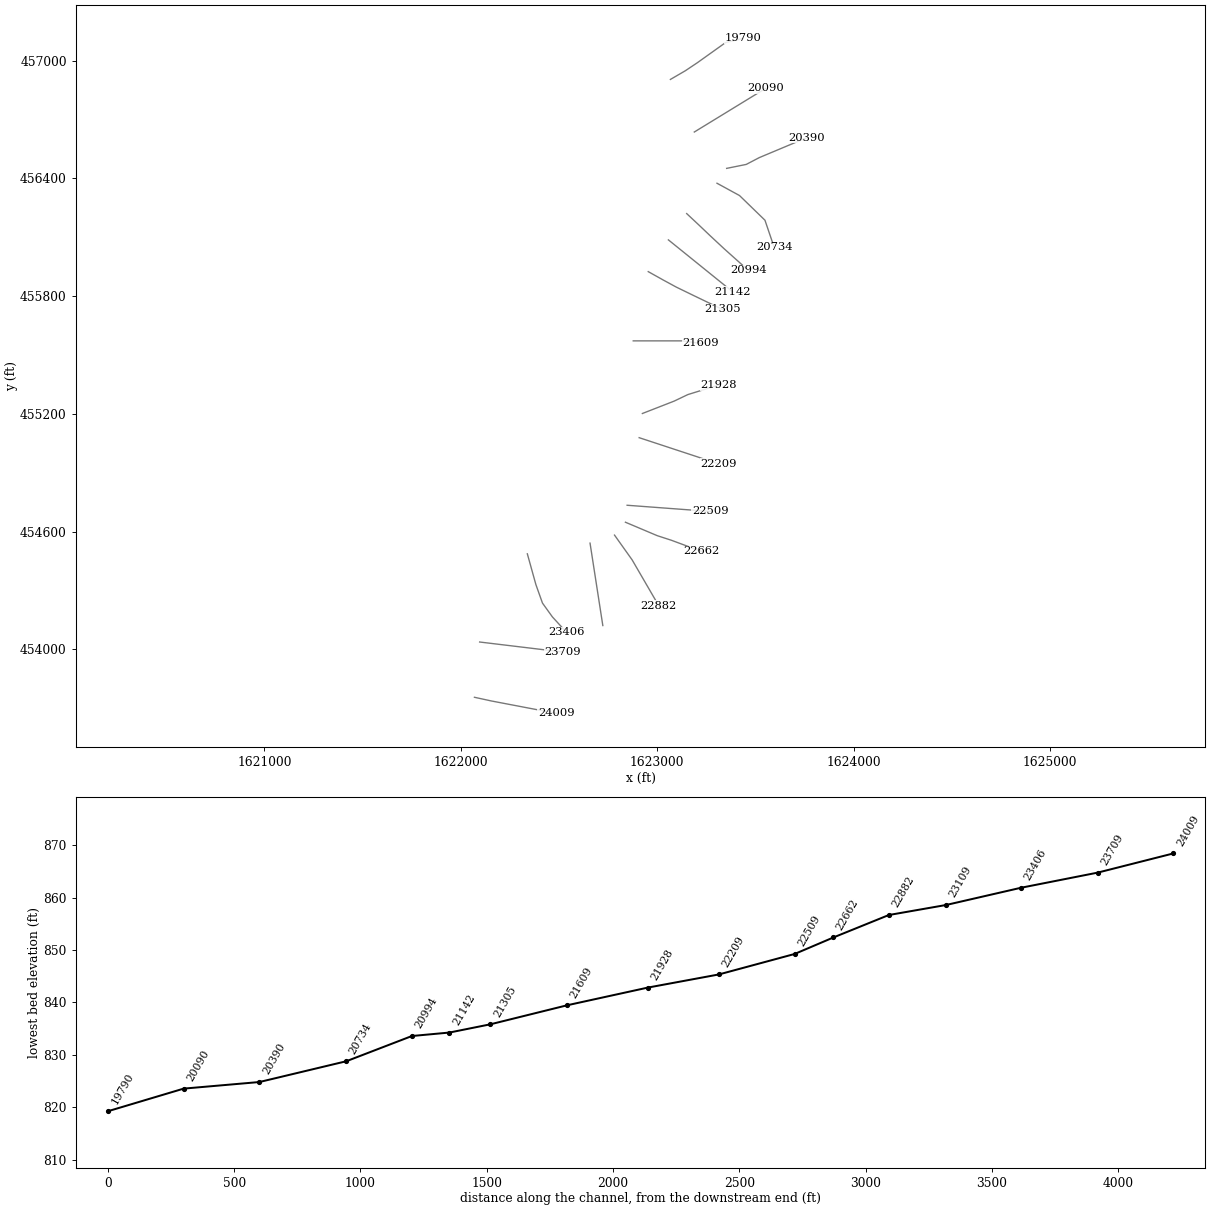
HEC-RAS study WhtstneCrk.prj: WhtstneCrk

--- WhtstneCrk.g01 (geometry) --- (continued)

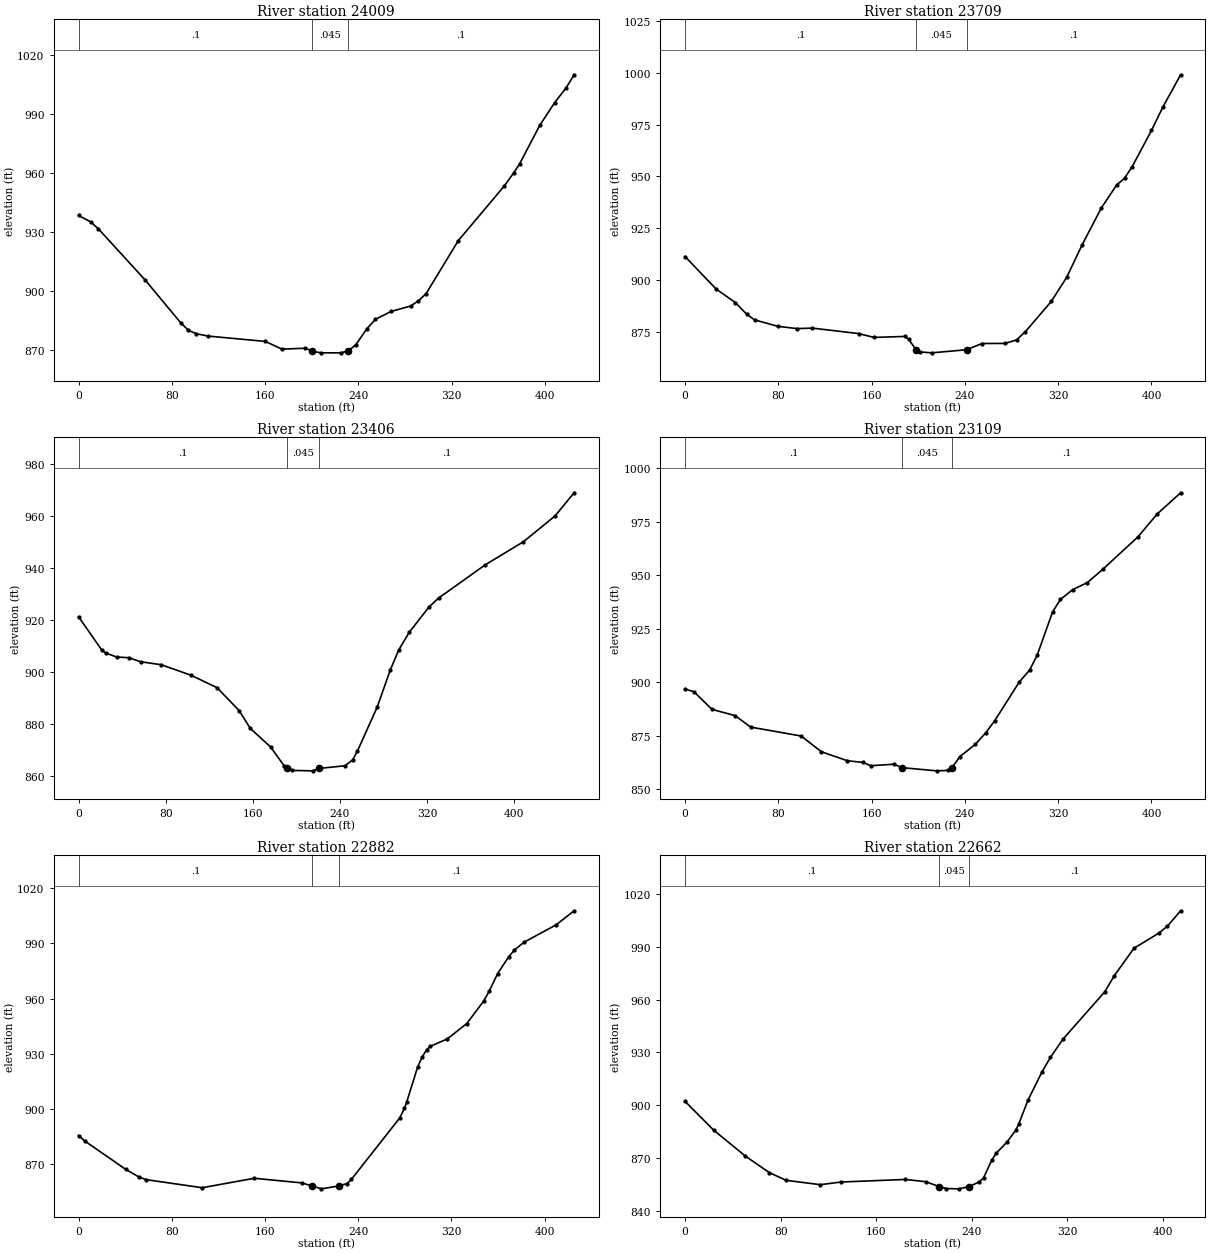
Type RM Length L Ch R = 1 ,24009   ,299.2,300,301
XS GIS Cut Line= 6
1622069.47652958453756.0471820831622154.99177851 453737.37595959
1622228.65829784453723.2956071791622326.88021426453704.521366507
1622400.54640551453690.4406860021622486.49045934  453674.0135535
#Sta/Elev= 30
       0  938.25    10.4     935    17.1  931.42    57.4  905.31    87.5  883.82
    94.3  879.89     101  878.19     111     877   160.2  874.27   174.5  870.34
   194.5  870.83  200.34869.3889   207.8  868.47   224.7  868.47  231.35869.3882
   237.9  872.66   247.1  880.58   254.6  885.48     268  889.48   284.7  892.24
   291.4  894.82   298.1  898.57   325.6  925.41   364.9  953.08   373.1  959.79
   378.2  964.41   395.7  984.18   408.3  995.56   418.2 1003.12     425 1009.72
#Mann= 3 ,-1,0
       0      .1       0  200.34    .045       0  231.35      .1       0
Bank Sta=200.34,231.35
XS Rating Curve= 0 ,0
Exp/Cntr(USF)=0,0
Exp/Cntr=0.3,0.1

Type RM Length L Ch R = 1 ,23709   ,324.9,303.5,290.8
XS GIS Cut Line= 6
1622095.90134551454037.5971439181622182.77223475454027.123411596
1622257.23304383454018.1460673361622356.51401326   454006.176275
1622430.97449426453997.1989307551622517.84538351453986.725198418
#Sta/Elev= 30
       0  911.29    26.6  895.63    43.1  889.08      53  883.38    59.6  880.72
    79.4  877.61      96   876.5   109.2  876.74   148.8   874.1   162.1  872.25
   188.5  872.72   191.8  871.31  198.13   866.3   201.7  865.23   211.6   864.8
  241.59 866.303   254.6   869.3   274.4  869.35   284.3  871.03   291.8     875
   314.1  889.61   327.3  901.27   340.4   916.8     357  934.76   370.2  945.89
   376.9   949.1   383.5  954.74     400  972.16   409.9  983.59     425  999.03
#Mann= 3 ,-1,0
       0      .1       0  198.13    .045       0  241.59      .1       0
Bank Sta=198.13,241.59
XS Rating Curve= 0 ,0
Exp/Cntr(USF)=0,0
Exp/Cntr=0.3,0.1

Type RM Length L Ch R = 1 ,23406   ,300.1,296.5,294.7
XS GIS Cut Line= 6
1622338.74501993454486.8275446741622362.16426443454402.519970506
  1622382.237387454330.2560074181622415.83213609454235.801471919
 1622466.4304601454165.3636206691622537.60223375454087.635429665
#Sta/Elev= 30
       0  921.15    21.5  908.26    24.9  907.21    35.1  905.64    46.2   905.4
    56.9  903.85      76  902.69   103.2  898.67   127.1  893.89   147.5  885.05
   157.7  878.21   176.3   871.1   188.9  863.74  191.49 862.844   195.9  862.07
   214.8  861.91  221.04862.8445   244.7  863.87   251.6  866.12   255.9  869.41
   274.1  886.37   286.2  900.68   293.8  908.27   303.5  915.12   321.9     925
   330.6  928.34   373.2  941.06   408.3  949.95   437.4  959.88   454.9  968.79
#Mann= 3 ,-1,0
       0      .1       0  191.49    .045       0  221.04      .1       0
Bank Sta=191.49,221.04
XS Rating Curve= 0 ,0
Exp/Cntr(USF)=0,0
Exp/Cntr=0.3,0.1

Type RM Length L Ch R = 1 ,23109   ,218.8,227.1,230.7
XS GIS Cut Line= 6
1622657.97502451454541.4219236671622671.37165126454454.953592673
1622682.85456793454380.8379272521622698.16490476 454282.01693067
1622709.64782143454207.9012652491622723.04444817454121.432606176
#Sta/Elev= 30
       0   896.9     7.7  895.57    23.1  887.37      43  884.42    56.3  879.06
    99.5  874.92   116.9  867.55   139.3  863.33   152.6  862.56   159.2  861.01
   179.1  861.71   186.2860.1121   215.7  858.62   225.6  858.83  228.94 860.112
   235.6  865.24   248.9  870.99   257.8  876.36   265.5     882   286.5  900.06
   295.6  905.84     302  912.73   315.2  932.94   321.9  938.75   332.5  943.37
   345.1  946.67   358.4  952.94   388.3  967.97   404.9  978.74     425  988.64
#Mann= 3 ,-1,0
       0      .1       0   186.2    .045       0  228.94      .1       0
Bank Sta=186.2,228.94
XS Rating Curve= 0 ,0
Exp/Cntr(USF)=0,0
Exp/Cntr=0.3,0.1

Type RM Length L Ch R = 1 ,22882   ,211.2,219.6,228.8
XS GIS Cut Line= 3
1622782.54456613454582.2778793651622872.23027057454456.115814493
1623008.10964473 454222.05988313
#Sta/Elev= 30
       0  885.63     5.7  882.55    40.4  867.33    52.1  863.06      58   861.7
   106.2  857.31   150.9  862.44   191.7  859.93  200.59 858.252   208.5   856.7
  223.27858.2511   230.5  859.58   234.3   861.9   275.7  895.18   279.8  900.45
   281.6  903.64   291.2  923.11   294.9  928.17   298.8  932.31   302.1  934.19
   316.5  938.13   333.3  946.51   347.7  958.63   352.5  964.05   359.7  973.55
   369.3  982.81   374.1  986.37   382.2   990.6   410.1 1000.17   425.4 1007.76
#Mann= 3 ,-1,0
       0      .1       0  200.59    .045       0  223.27      .1       0
Bank Sta=200.59,223.27
XS Rating Curve= 0 ,0
Exp/Cntr(USF)=0,0
Exp/Cntr=0.3,0.1

Type RM Length L Ch R = 1 ,22662   ,152.4,153.3,158.4
XS GIS Cut Line= 4
1622838.18966993454647.8547079181622999.69958371454579.516465359
1623072.28942782454555.8825626261623225.14098746  454499.1875949
#Sta/Elev= 30
       0  902.17    24.2  885.64    50.5  871.04    70.5  861.64    84.7  857.24
   113.2  854.78   130.6  856.29   184.2  857.75   201.5  856.47  212.71853.6718
   218.7  852.58   229.1  852.41  237.69853.6709   246.3  856.43   249.8  858.65
   256.7  868.78   260.2  872.55   269.1  878.79   276.7  885.68   279.3  889.38
   286.9  902.76   298.7  918.93   305.7  927.13   316.2  937.51   351.2  964.47
   358.9  973.37   375.7  989.29   396.7  997.96   403.7 1001.88   414.7 1010.57
#Mann= 3 ,-1,0
       0      .1       0  212.71    .045       0  237.69      .1       0
Bank Sta=212.71,237.69
XS Rating Curve= 0 ,0
Exp/Cntr(USF)=0,0
Exp/Cntr=0.3,0.1

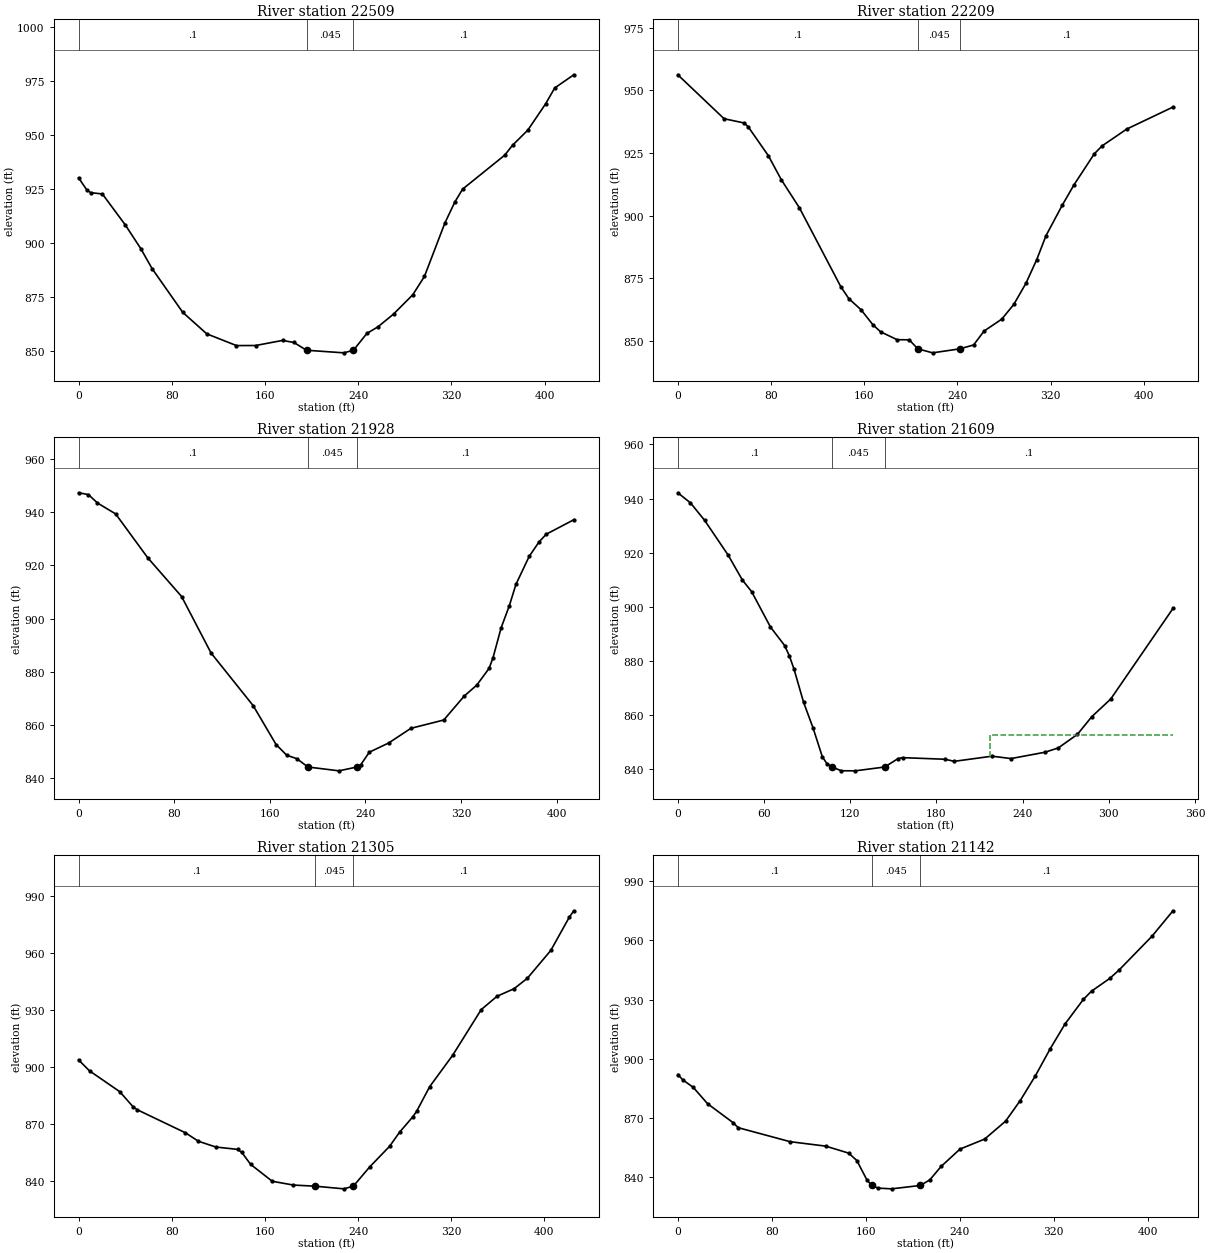
Type RM Length L Ch R = 1 ,22509   ,302.7,300,293.3
XS GIS Cut Line= 6
1622846.72366276454734.3158948421622933.98103417454727.804096833
1623008.77320743454722.2220870111623108.49577701454714.779844671
1623183.28762217454709.1981629281623270.54499359 454702.68603684
#Sta/Elev= 30
       0  930.26     7.2  924.54    10.5  923.41    20.4  922.81    40.1  908.46
    53.3  897.55    63.1  888.22    89.4  867.99     110  858.05   135.5  852.62
   151.9  852.65     175  855.01   184.8  854.05   195.6 850.461   227.6  849.26
  235.88850.4612   247.4  858.24     257  861.33   270.4  867.26   286.8  876.14
   296.8  884.62   314.4  909.41     323  919.17   329.6  925.06   365.8  940.81
   372.4  945.35   385.5  952.34   400.9  964.61   408.6  971.87     425  977.99
#Mann= 3 ,-1,0
       0      .1       0   195.6    .045       0  235.88      .1       0
Bank Sta=195.6,235.88
XS Rating Curve= 0 ,0
Exp/Cntr(USF)=0,0
Exp/Cntr=0.3,0.1

Type RM Length L Ch R = 1 ,22209   ,267.3,281.2,296.8
XS GIS Cut Line= 6
1622908.04145351455078.5940776771622991.14857076455051.218148172
1623062.38333642455027.7529720071623157.36313334454996.466289178
  1623228.597899454973.0011130121623311.70501626454945.625183508
#Sta/Elev= 30
       0  956.25    39.7  938.73      57  937.02    60.4  935.52    77.7  923.99
    88.8  914.42   104.4  903.18   139.9  871.73   146.8  866.95   157.2  862.57
   167.5  856.52   174.1  853.73   188.2   850.6   198.6  850.54  206.02846.9427
   218.7  845.35   242.1846.9425   253.9   848.5   262.9  854.05   278.1  858.81
   288.4  864.67   298.8  873.08   308.1  882.56     316  892.05   329.9  904.18
   340.2  912.47   357.5  924.74   364.2   927.9   385.3  934.59     425  943.38
#Mann= 3 ,-1,0
       0      .1       0  206.02    .045       0   242.1      .1       0
Bank Sta=206.02,242.1
XS Rating Curve= 0 ,0
Exp/Cntr(USF)=0,0
Exp/Cntr=0.3,0.1

Type RM Length L Ch R = 1 ,21928   ,326.5,318.8,310
XS GIS Cut Line= 4
1622924.52304783455201.7762460111623086.44385091 455264.95359155
1623155.91446447455298.1451069171623312.20168729455346.551323046
#Sta/Elev= 30
       0  947.32     8.2  946.64    15.8  943.48      31  939.37      58  922.81
    86.2  908.34   110.8  887.14   146.1  867.33   165.3   852.7   174.2   848.7
   182.7  847.39  191.89 844.283   217.9  842.84  232.95844.2842   236.1  845.11
   243.3  849.85   259.5  853.31   278.1  858.82   305.6  861.94   322.7  870.93
   333.2  875.05   343.5  881.33   346.8  885.32   353.6  896.58   360.5  904.94
     366  912.92   377.1  923.44   385.4   928.9   391.4  931.76   414.4  937.18
#Mann= 3 ,-1,0
       0      .1       0  191.89    .045       0  232.95      .1       0
Bank Sta=191.89,232.95
XS Rating Curve= 0 ,0
Exp/Cntr(USF)=0,0
Exp/Cntr=0.3,0.1

Type RM Length L Ch R = 1 ,21609   ,311,304.3,293.5
XS GIS Cut Line= 5
1622877.93685493455571.7820676711622952.93703301455571.782067671
1623052.93716109455571.7820676711623127.93701109455571.782067671
1623221.64482893455558.690558419
#Sta/Elev= 30
       0  942.13     8.8  938.41    18.6     932      35  919.15    44.9  909.96
    51.4  905.61    64.5  892.55    74.4   885.7    77.7  881.83    80.9  876.99
    87.5  864.84    94.1  855.35   100.6  844.63   103.9  842.04  107.26840.8918
   113.8   839.5   123.5  839.47  144.06840.8904   153.1  843.94   156.4  844.34
   185.9  843.75   192.4  842.98   218.7  844.88   231.9     844   255.6  846.35
   264.8  847.94   278.1  852.93     288  859.41   301.3     866   344.6  899.42
#Mann= 3 ,-1,0
       0      .1       0  107.26    .045       0  144.06      .1       0
#XS Ineff= 2 , 0
                          217.08          852.65
Permanent Ineff=
       F       F
Bank Sta=107.26,144.06
XS Rating Curve= 0 ,0
Exp/Cntr(USF)=0,0
Exp/Cntr=0.3,0.1

Type RM Length L Ch R = 1 ,21305   ,165.6,162.8,154.9
XS GIS Cut Line= 6
1622954.30218776455924.4821496751623030.82532868 455881.71615909
1623096.79730959455845.8504171671623186.71740533455802.094599172
1623254.29240142455769.5585750041623333.13017026455731.599989504
#Sta/Elev= 30
       0  903.77     9.4  898.01    35.3  887.07    46.6  879.22    50.3  877.54
    91.7  865.39   102.9  860.92   117.8  857.88   136.5  856.63   140.2  855.01
   147.7  848.75   166.3  839.82   184.5  837.82  203.12837.2331   227.8  835.83
  235.97837.2357   249.9  847.31   267.1  858.25   275.7   865.7   287.1  873.85
   290.3  876.68   301.5  889.67   321.2  906.18   345.8  930.31   359.4  937.35
     374  941.33   385.4  946.82   405.6  961.54   421.4  978.98   425.3  982.41
#Mann= 3 ,-1,0
       0      .1       0  203.12    .045       0  235.97      .1       0
Bank Sta=203.12,235.97
XS Rating Curve= 0 ,0
Exp/Cntr(USF)=0,0
Exp/Cntr=0.3,0.1

Type RM Length L Ch R = 1 ,21142   ,149.4,148.3,145.9
XS GIS Cut Line= 2
1623056.86298624456086.3215653711623384.68042197455821.399335335
#Sta/Elev= 30
       0   892.1     4.4  889.35    13.2   885.6    25.3  877.36      47  867.78
    51.4  865.21    95.6  858.12   125.9  855.87   145.4  852.34   152.4  848.59
   160.9  838.84  165.12835.9604   170.3  834.62     182  834.25   206.5 835.962
   214.6  838.84   224.1  845.56   240.2  854.37   261.2  859.44     279   868.5
   291.5  878.95   304.3  891.39   316.9  905.05   329.6   917.7   345.2  930.13
   352.2  934.33   367.6  940.73   375.6     945   403.6   962.1   421.5  975.01
#Mann= 3 ,-1,0
       0      .1       0  165.12    .045       0   206.5      .1       0
Bank Sta=165.12,206.5
XS Rating Curve= 0 ,0
Exp/Cntr(USF)=0,0
Exp/Cntr=0.3,0.1

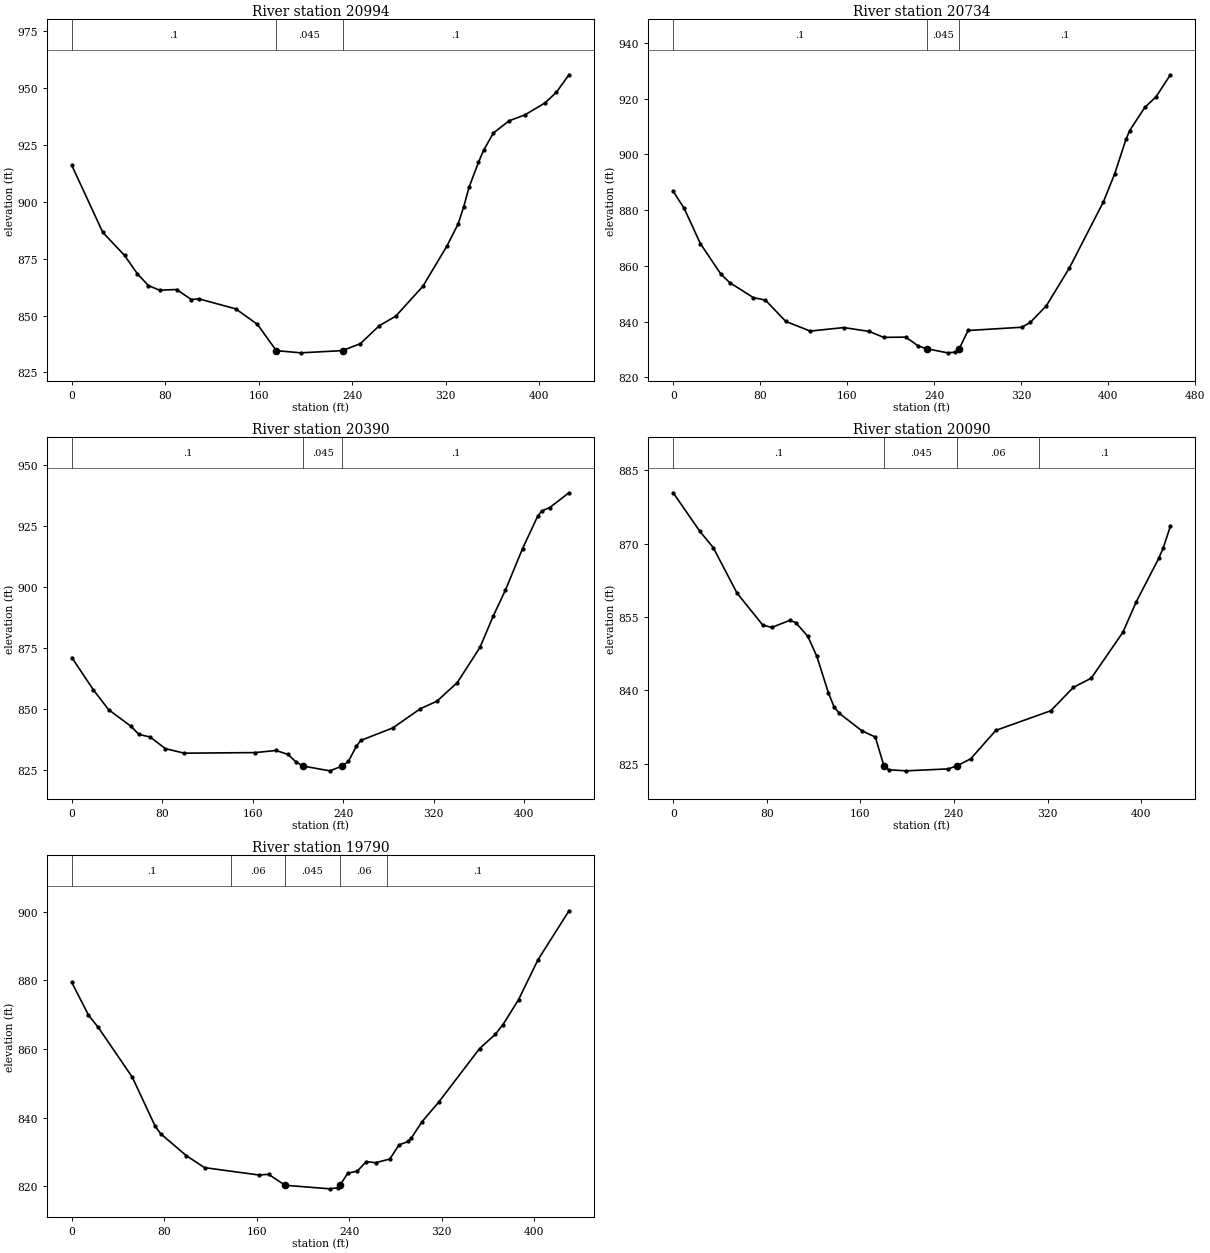
Type RM Length L Ch R = 1 ,20994   ,259.2,259.8,252.4
XS GIS Cut Line= 6
1623150.01997218456220.2597733441623213.86236417456160.465273499
1623268.13259684456108.7189859151623341.37129551456040.509804755
 1623397.4026795455990.3452069161623462.92354584455931.965730503
#Sta/Elev= 30
       0  916.01    26.5  886.57    45.1  876.44      56  868.44    65.6  863.15
    75.2  861.13    89.6  861.45   102.3  857.03   108.6  857.36   140.2  852.94
   158.8  846.15  174.99834.5637   195.9  833.59  231.66 834.564     247  837.66
   263.2  845.55   277.2  849.71   300.4  862.84     321  880.55   330.6  890.26
   335.3  897.66   339.9  906.33     348  917.37   352.4  922.68   360.8   930.3
   374.4   935.7   387.6  938.21     405  943.52   414.7  948.21   425.5   955.9
#Mann= 3 ,-1,0
       0      .1       0  174.99    .045       0  231.66      .1       0
Bank Sta=174.99,231.66
XS Rating Curve= 0 ,0
Exp/Cntr(USF)=0,0
Exp/Cntr=0.3,0.1

Type RM Length L Ch R = 1 ,20734   ,318.5,344.1,357.2
XS GIS Cut Line= 4
1623304.38632439 456374.82858774 1623418.9868978456312.172531264
1623548.58913983456186.3821198811623595.47295487456048.160468969
#Sta/Elev= 30
       0  886.78    10.1  880.59      25  867.95    43.7   857.1    51.9  853.98
    73.7  848.59    84.8  847.69   103.5  840.04     126  836.58   156.9  837.84
   180.4  836.44   193.5  834.32   213.9  834.41   225.5  831.19  232.97830.2663
   252.3  828.77   259.3  829.01  263.01830.2672   271.2  836.79   320.5  837.95
   328.3  839.66   343.2  845.69   364.4  859.28   395.6  882.94     406  893.02
   416.4  905.43   419.8  908.55   433.7  916.84   444.1  920.68   457.2  928.55
#Mann= 3 ,-1,0
       0      .1       0  232.97    .045       0  263.01      .1       0
Bank Sta=232.97,263.01
XS Rating Curve= 0 ,0
Exp/Cntr(USF)=0,0
Exp/Cntr=0.3,0.1

Type RM Length L Ch R = 1 ,20390   ,297.8,300,297.5
XS GIS Cut Line= 6
1623353.52940768456450.5785384181623453.20407709456470.709075585
1623519.92507225456505.5403707621623612.14470409 456544.21319367
1623681.30926393456573.2180569171623762.00135976456607.056571916
#Sta/Elev= 30
       0  871.24      19  858.02    32.5  849.87    52.4  843.02    59.3  839.73
    69.3  838.65    82.7   833.9    99.4  832.04   162.1  832.28   180.5  833.15
   191.2   831.5   198.3  828.37  204.37826.7674     228   824.8  239.18826.7689
   244.5  828.67   251.6  834.99   255.6  837.29   283.7  842.38   308.2  850.29
   322.8  853.36   340.8  861.01   360.8  875.43   372.6  888.32   383.3  898.88
   398.4  915.87   411.7  929.07   415.3   931.3   422.4   932.7   439.5  938.78
#Mann= 3 ,-1,0
       0      .1       0  204.37    .045       0  239.18      .1       0
Bank Sta=204.37,239.18
XS Rating Curve= 0 ,0
Exp/Cntr(USF)=0,0
Exp/Cntr=0.3,0.1

Type RM Length L Ch R = 1 ,20090   ,298.1,300,299.6
XS GIS Cut Line= 6
1623188.82468459456635.8084829151623263.44920726 456681.49703984
1623327.41299009456720.6587069181623412.69792451456772.874153674
1623476.66170734456812.0361488461623551.28623001456857.724377677
#Sta/Elev= 30
       0  880.44    22.7  872.58    34.3  869.19    54.5  859.93    76.6  853.35
    84.3  852.89    99.7  854.34   104.7  853.89   115.1  851.05   122.8  846.96
   132.6  839.55   137.4  836.69     142  835.31   161.2  831.75   172.8  830.45
  180.03824.6109   184.3  823.76     199  823.54   235.2  823.94  242.92824.6104
   254.3     826   275.8  831.82   322.8  835.84     342   840.6   357.4  842.51
   384.4  851.89   395.9  858.16   415.1  867.04     419   869.2     425  873.61
#Mann= 4 ,-1,0
       0      .1       0  180.03    .045       0  242.92     .06       0
   312.5      .1       0
Bank Sta=180.03,242.92
XS Rating Curve= 0 ,0
Exp/Cntr(USF)=0,0
Exp/Cntr=0.3,0.1

Type RM Length L Ch R = 1 ,19790   ,206.8,193,179.6
XS GIS Cut Line= 6
1623067.14382559456903.6924615951623143.11775501 456947.86953859
1623205.47294526456989.6073160021623286.84614208457047.731215507
1623347.87620376457091.3243041781623437.70870125457113.061793506
#Sta/Elev= 30
       0  879.42    14.4  869.88    22.8  866.35    52.3   851.8    72.1  837.52
    76.8  835.32    99.1  828.89   114.9   825.4   161.9  823.26   170.3  823.45
  184.55820.2634   223.3  819.22   230.3  819.55  232.04820.2631   238.9   823.8
   246.9  824.36     255  827.18   262.9  826.83   275.2  827.92   283.2  832.03
   291.3  833.07   293.8  834.02   303.2  838.85   317.4  844.46   352.9  860.13
   366.4  864.26   373.1   867.1   386.6  874.38   403.5  886.06   430.3  900.33
#Mann= 5 ,-1,0
       0      .1       0  137.88     .06       0  184.55    .045       0
  232.04     .06       0  272.92      .1       0
Bank Sta=184.55,232.04
XS Rating Curve= 0 ,0
Exp/Cntr(USF)=0,0
Exp/Cntr=0.3,0.1