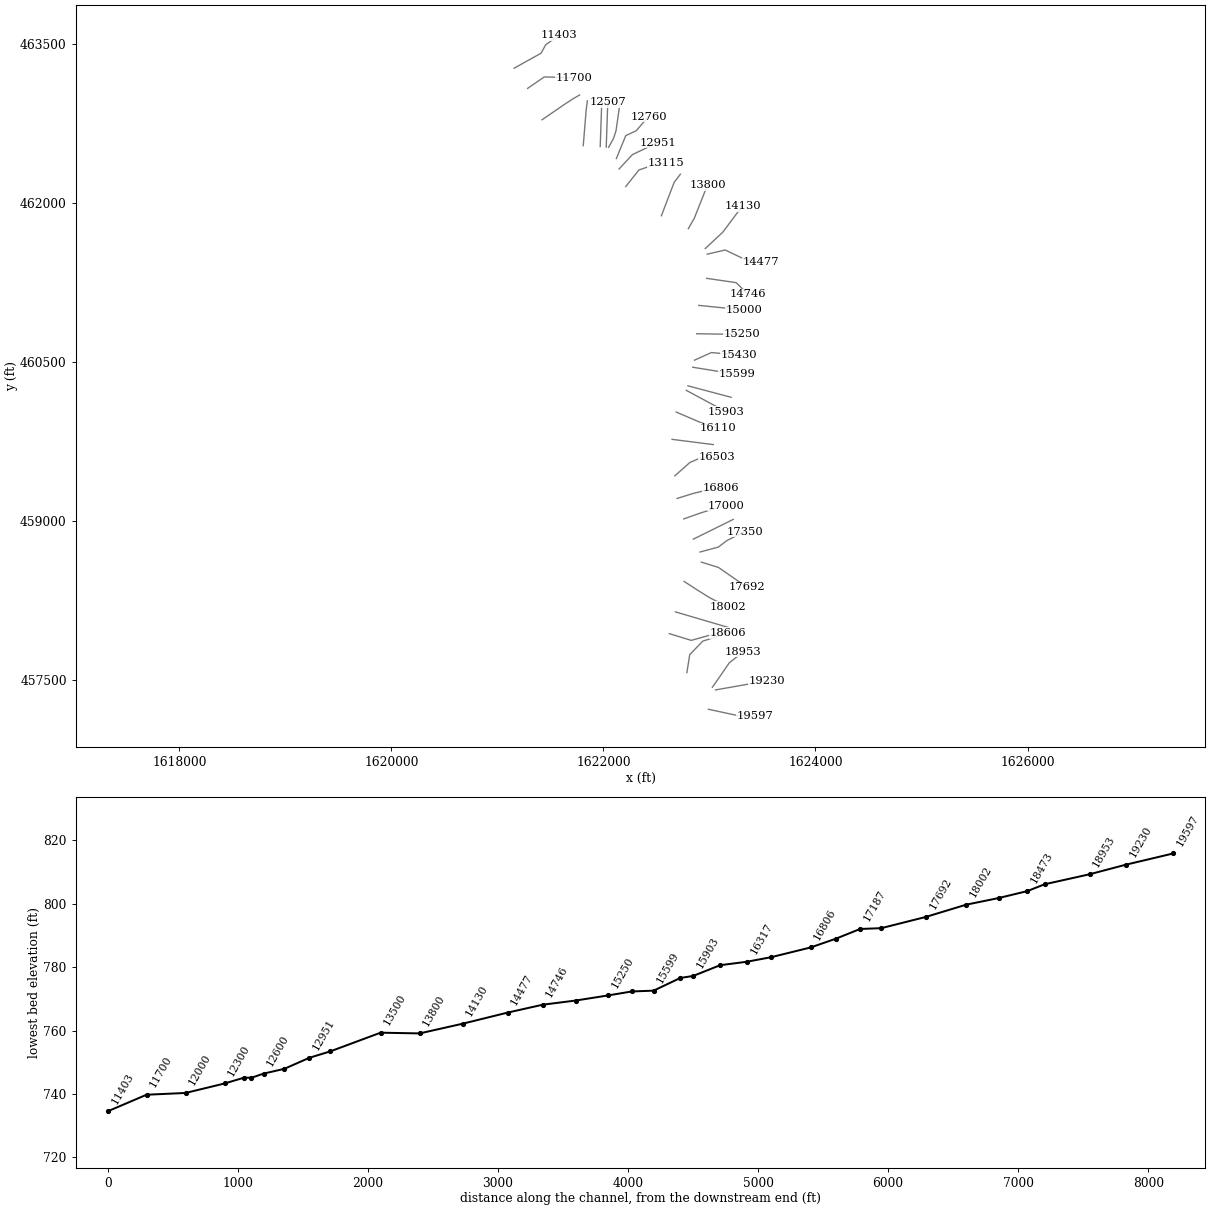
HEC-RAS study WhtstneCrk.prj: WhtstneCrk

--- WhtstneCrk.g01 (geometry) --- (continued)

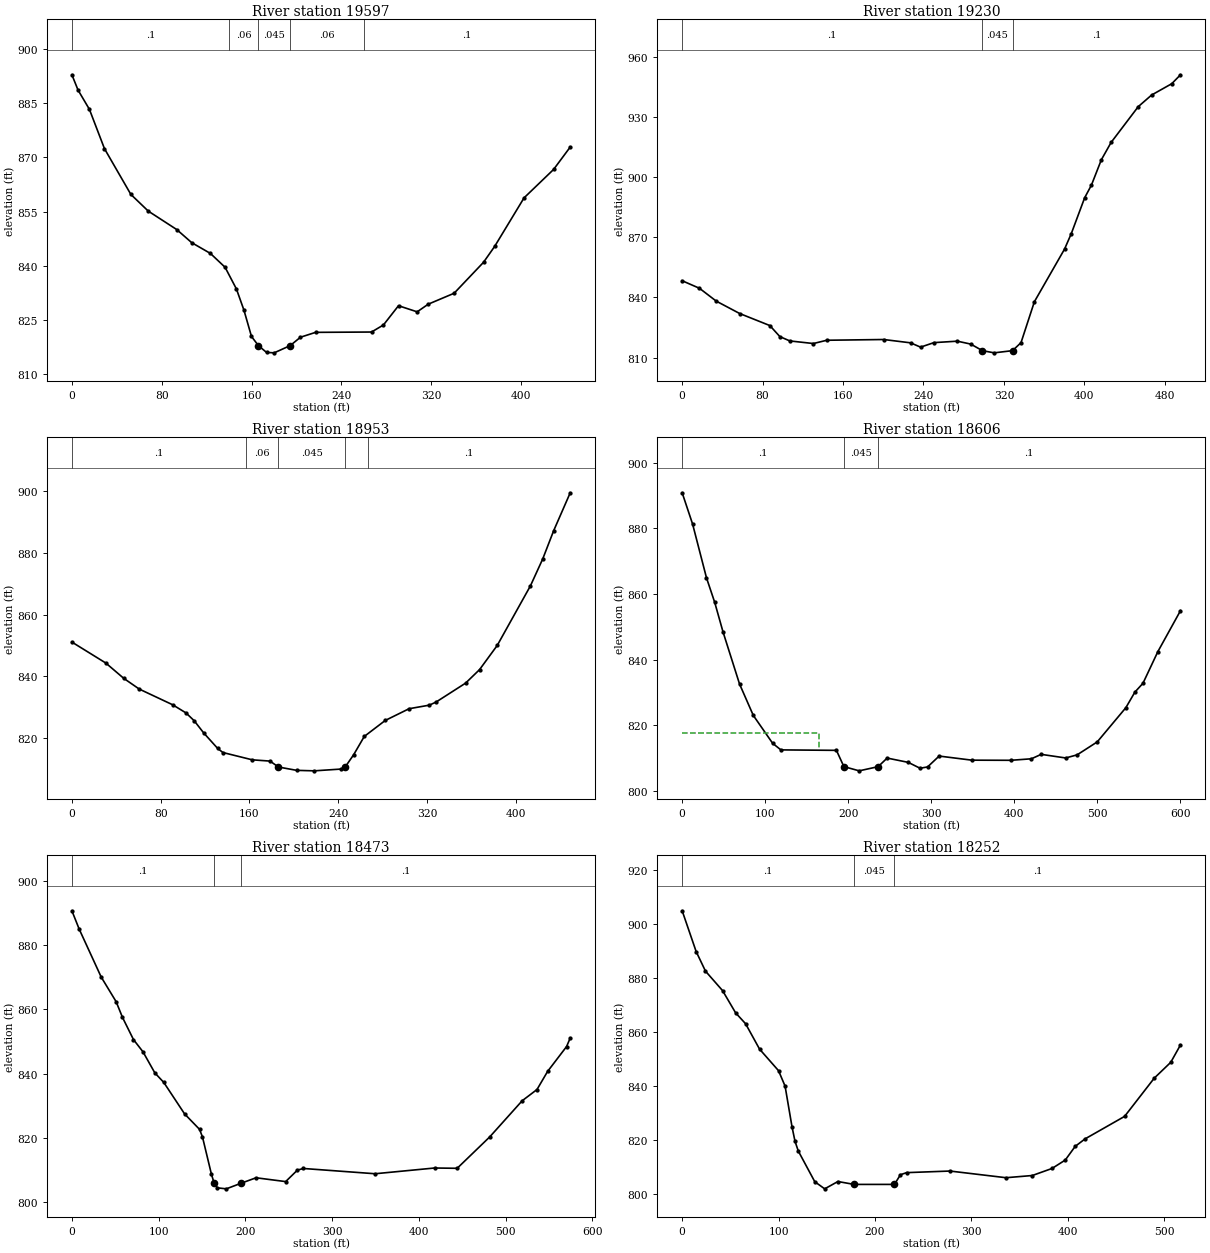
Type RM Length L Ch R = 1 ,19597   ,356.5,366.8,369.4
XS GIS Cut Line= 3
1622989.57427887457228.560257808 1623283.6669098457165.069638754
1623426.48529851457161.540043011
#Sta/Elev= 30
       0  892.88     5.5  888.63    15.6  883.31      29  872.43    52.5  859.77
      68  855.15    93.4  850.03   106.7  846.41   123.3  843.44   136.4   839.6
   146.5  833.59   153.2  827.72   159.9  820.45  166.08817.9177   173.3  816.04
   180.1  815.92  194.35817.9199   203.5  820.24     217  821.59   266.8  821.68
   277.4  823.64   290.8  828.96   307.4  827.27   317.3  829.39   340.3  832.41
   366.5  840.98   376.4  845.37   402.6  858.82   428.9  866.68   443.7  872.88
#Mann= 5 ,-1,0
       0      .1       0     140     .06       0  166.08    .045       0
  194.35     .06       0     260      .1       0
Bank Sta=166.08,194.35
XS Rating Curve= 0 ,0
Exp/Cntr(USF)=0,0
Exp/Cntr=0.3,0.1

Type RM Length L Ch R = 1 ,19230   ,263.9,277.5,285.7
XS GIS Cut Line= 2
1623056.76359701457410.823993251 1623544.8621102457496.673397118
#Sta/Elev= 30
       0  848.27    17.2  844.52    33.9  838.12    57.2  831.94    87.2  825.94
    97.2  820.42   107.1  818.28   130.5  816.99   143.8  818.62   200.4  818.99
   227.1  817.34   237.1  815.19   250.4  817.44   273.7  818.16     287  816.71
  298.57813.4402   310.3  812.35  328.58813.4409     337  817.44   350.3  837.83
   380.3  864.06     387  871.76   400.3  889.64     407   895.9   416.9  908.57
   426.6   917.2   453.6  935.03   466.9  940.82   486.9  946.45   495.6   950.9
#Mann= 3 ,-1,0
       0      .1       0  298.57    .045       0  328.58      .1       0
Bank Sta=298.57,328.58
XS Rating Curve= 0 ,0
Exp/Cntr(USF)=0,0
Exp/Cntr=0.3,0.1

Type RM Length L Ch R = 1 ,18953   ,350.9,346.7,346.8
XS GIS Cut Line= 4
1623027.29274773457436.411555885 1623088.7838434457523.836029413
1623187.04912828457666.5418576031623319.57710914457771.352651143
#Sta/Elev= 30
       0  851.12    30.6  844.31    46.7  839.36    60.7  835.87    90.8  830.78
   102.8  828.14   110.2   825.6   118.8  821.63   131.4   816.6   136.1  815.28
   162.6  812.91   178.6   812.5  186.09810.5864   202.5   809.5   218.4  809.34
   242.3  809.91  246.28810.5859   253.9  814.55   263.5   820.5   282.4  825.69
   303.9   829.5   322.1  830.65   328.1  831.64   354.8   837.8   367.4  842.19
   383.3  850.02   413.2  869.34   424.3  878.08   434.2  887.28   449.1  899.56
#Mann= 5 ,-1,0
       0      .1       0  156.88     .06       0  186.09    .045       0
  246.28     .06       0  266.88      .1       0
Bank Sta=186.09,246.28
XS Rating Curve= 0 ,0
Exp/Cntr(USF)=0,0
Exp/Cntr=0.3,0.1

Type RM Length L Ch R = 1 ,18606   ,152.1,132.8,114
XS GIS Cut Line= 4
1622786.86889553457573.6545033771622813.70076293457743.559220165
1622936.65119089457870.7726392421623175.74357532457948.113964398
#Sta/Elev= 30
       0  890.86    12.6   881.3    29.3  864.95    39.2  857.48    49.2  848.49
    69.1  832.62    85.7  823.04     109  814.55   118.9  812.55   185.8  812.41
  194.79807.4587   213.2  806.17     236  807.44   246.9  810.06   272.3  808.75
   286.5  806.96   295.6  807.36   309.5  810.67   348.9  809.42   395.9  809.38
   420.6  809.84   432.4  811.19   461.9  810.09   475.7  811.04   499.9  814.98
   534.4  825.41   545.3  830.16     555  832.84     573  842.51   600.2  854.96
#Mann= 3 ,-1,0
       0      .1       0  194.79    .045       0     236      .1       0
#XS Ineff= 2 , 0
          164.26  817.74
Permanent Ineff=
       F       F
Bank Sta=194.79,236
XS Rating Curve= 0 ,0
Exp/Cntr(USF)=0,0
Exp/Cntr=0.3,0.1

Type RM Length L Ch R = 1 ,18473   ,218.6,221.4,219.9
XS GIS Cut Line= 3
1622621.42362851457941.633510185 1622828.1201454457878.166529895
1623172.90022752457975.082324121
#Sta/Elev= 30
       0  890.78     8.4  885.06    33.8  870.09      51  862.41    58.3  857.52
      71  850.58    81.9  846.79    95.6   840.2   105.9  837.23   129.9   827.4
   147.1  822.59   150.5  820.22   160.8  808.62  163.96805.7946   167.7  804.33
     178  804.02  195.19805.7862   212.3  807.47   246.4  806.28     260  809.88
   266.9  810.37   349.5  808.73     418  810.52   444.1  810.43   481.6  820.22
     519   831.5   536.1  835.01   548.3  840.65   570.2  848.42   574.4  851.09
#Mann= 3 ,-1,0
       0      .1       0  163.96    .045       0  195.19      .1       0
Bank Sta=163.96,195.19
XS Rating Curve= 0 ,0
Exp/Cntr(USF)=0,0
Exp/Cntr=0.3,0.1

Type RM Length L Ch R = 1 ,18252   ,250.8,249.7,237.2
XS GIS Cut Line= 2
1622679.22985444458146.8709765761623175.28534051458000.891749375
#Sta/Elev= 30
       0  904.78    14.5  889.69    24.2  882.43    41.9  875.23    55.5  866.97
    65.8  862.96    80.3  853.56     100  845.57   106.8  839.85     114  824.75
   117.1  819.42   120.5  815.82   137.6  804.46   147.9  801.82   161.6  804.53
  178.43803.4586  220.27803.4622   226.5  807.04   232.9  807.82   277.9  808.41
     336  805.94   363.3  806.75   383.8  809.37   397.5  812.47   407.8  817.53
     418   820.3   459.1  828.65   489.9  842.82     507  848.67   517.1  855.12
#Mann= 3 ,-1,0
       0      .1       0  178.43    .045       0  220.27      .1       0
Bank Sta=178.43,220.27
XS Rating Curve= 0 ,0
Exp/Cntr(USF)=0,0
Exp/Cntr=0.3,0.1

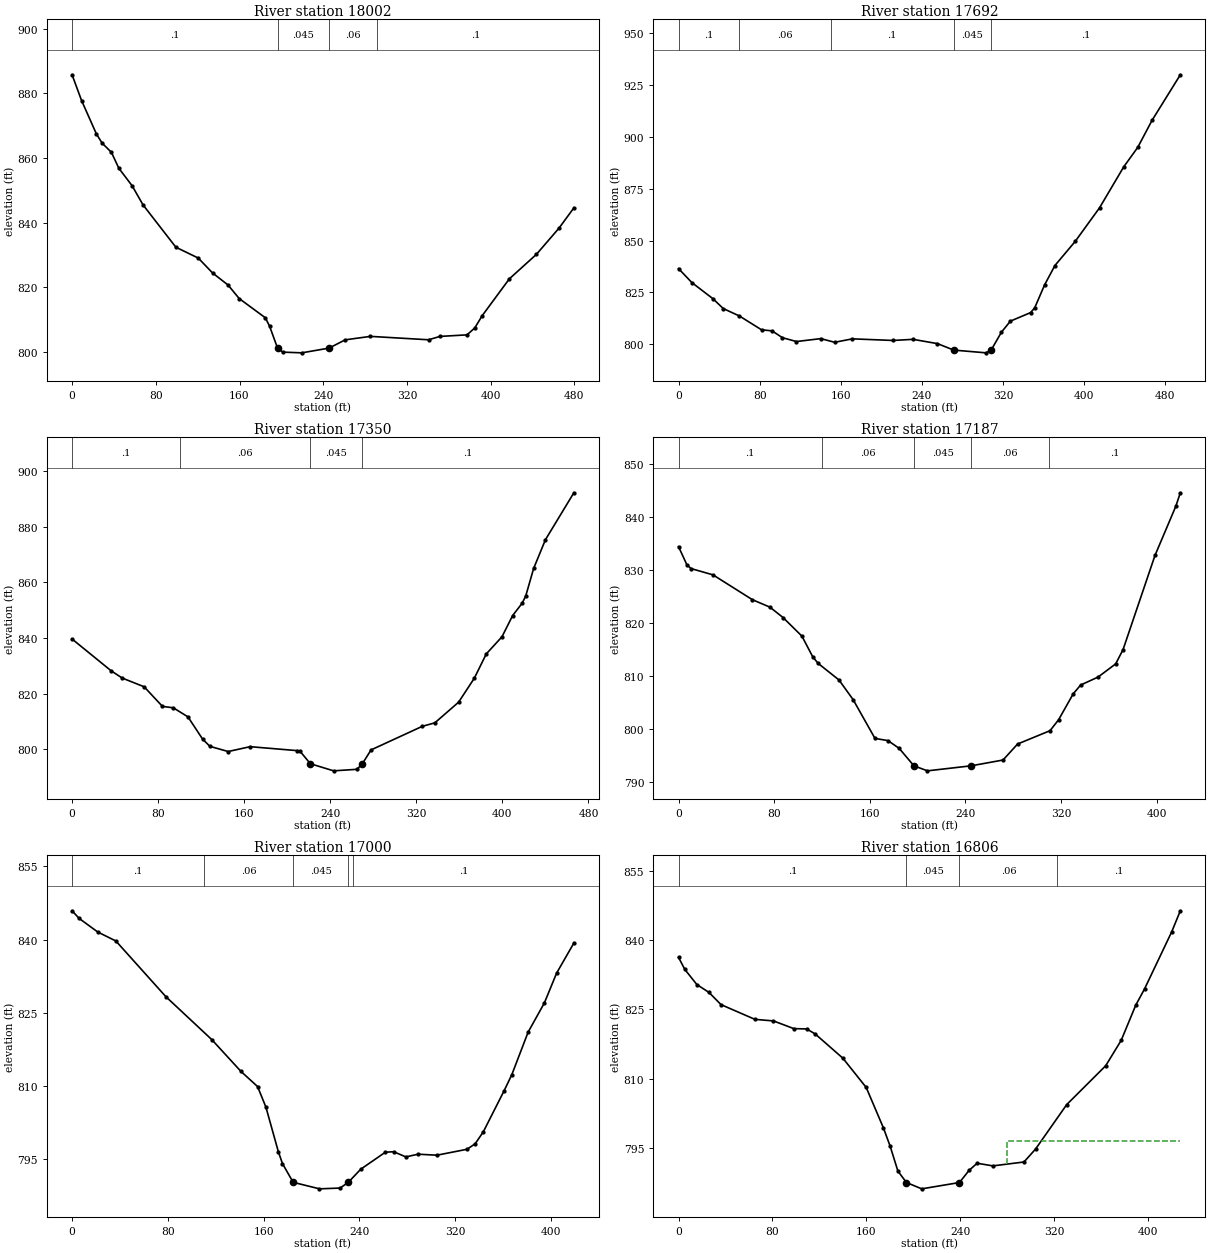
Type RM Length L Ch R = 1 ,18002   ,304.8,309.5,297.9
XS GIS Cut Line= 5
1622760.90756142458434.2218808381622834.31653534458386.604850084
1622897.23865359458345.7906272561623006.86466812458278.030037494
1623174.60477373458192.759222477
#Sta/Elev= 30
       0  885.71     9.1  877.73    23.3  867.38    28.7  864.59    37.6  861.72
    44.7   856.8    57.3  851.43    67.8  845.48    99.2  832.38   120.6  829.03
   134.3  824.41   149.1  820.68   159.7  816.51   184.6  810.58   188.7     808
  196.34801.1885   201.4  799.94   219.5  799.72  245.63801.1878     261  803.74
   285.1  804.81   340.6  803.76   351.6   804.8   377.4  805.28   384.8  807.41
   391.9  811.21   417.9  822.62   443.7  830.17   465.3  838.28   479.5  844.54
#Mann= 4 ,-1,0
       0      .1       0  196.34    .045       0  245.63     .06       0
  291.38      .1       0
Bank Sta=196.34,245.63
XS Rating Curve= 0 ,0
Exp/Cntr(USF)=0,0
Exp/Cntr=0.3,0.1

Type RM Length L Ch R = 1 ,17692   ,306.1,342.6,358.6
XS GIS Cut Line= 3
1622923.29454396 458616.407687451623085.12377651458566.239333332
1623352.43242213 458380.56246149
#Sta/Elev= 30
       0  836.49    13.2  829.72    33.8  822.02    44.1  817.22      60  813.64
    81.9  806.96    92.2  806.47   102.5  803.16   116.3  801.31   140.3  802.72
     154  800.95   171.5  802.61   211.5  801.83   231.3  802.37   255.4   800.3
  271.41 797.189   303.3  795.86  308.32797.1874   318.5  805.84   327.3  811.15
   347.3  815.28   351.3  817.59     361   828.6   371.2  837.97   391.2  849.59
   415.2  865.79   439.1  885.58   452.9  894.95     467  907.99   494.9  929.97
#Mann= 5 ,-1,0
       0      .1       0      60     .06       0     150      .1       0
  271.41    .045       0  308.32      .1       0
Bank Sta=271.41,308.32
XS Rating Curve= 0 ,0
Exp/Cntr(USF)=0,0
Exp/Cntr=0.3,0.1

Type RM Length L Ch R = 1 ,17350   ,166.2,162.8,157.2
XS GIS Cut Line= 4
1622910.63458538458711.555998817 1623083.8671122 458758.27698581
 1623166.7744288458821.1721915021623330.17550471 458903.30245821
#Sta/Elev= 30
       0  839.68    36.4  828.24    46.6  825.66      67  822.52      84  815.48
    94.1  814.97   107.7  811.72   121.3  803.74   128.1  801.12   145.1  799.26
   165.5     801     209  799.59     212  799.31   221.5794.8723   243.1  792.32
   264.8  792.87   269.6  794.74   277.9  799.84   325.5  808.31   337.2  809.57
   359.3     817   373.9  825.62     385  834.33   399.6   840.5   409.5  848.11
   418.4  852.58   421.7  855.18     429  865.03     440  875.38   466.4  892.23
#Mann= 4 ,-1,0
       0      .1       0     100     .06       0   221.5    .045       0
   269.6      .1       0
Bank Sta=221.5,269.6
XS Rating Curve= 0 ,0
Exp/Cntr(USF)=0,0
Exp/Cntr=0.3,0.1

Type RM Length L Ch R = 1 ,17187   ,190,187.4,182.9
XS GIS Cut Line= 2
1622847.75673963458833.0041366761623223.90948735459019.165124196
#Sta/Elev= 30
       0  834.35       7  830.92    10.5  830.21    28.8  829.03    61.8  824.34
    76.4  822.94    87.4  820.98   103.2  817.47   112.2  813.59   116.7  812.34
   134.2   809.2     146   805.5   164.3  798.18   175.2  797.76   184.6  796.29
  196.86  793.01   208.2  792.06   244.8  793.01   271.4   794.1   283.6  797.12
   310.7  799.63   317.9   801.7   330.1  806.58   336.3  808.24   350.9  809.75
   365.6  812.23   371.8  814.93   398.5  832.69   415.9  841.95   419.7  844.51
#Mann= 5 ,-1,0
       0      .1       0     120     .06       0  196.86    .045       0
   244.8     .06       0     310      .1       0
Bank Sta=196.86,244.8
XS Rating Curve= 0 ,0
Exp/Cntr(USF)=0,0
Exp/Cntr=0.3,0.1

Type RM Length L Ch R = 1 ,17000   ,194.8,193.5,191.5
XS GIS Cut Line= 4
1622757.08314927459023.7863004961622912.07641879459078.655484991
1623010.10717348459109.5313132391623156.53335361459149.739773525
#Sta/Elev= 30
       0   845.9     5.9  844.34    21.4  841.56    36.6  839.71    78.3  828.32
   116.6  819.54     141  813.02   154.9  809.91   161.9  805.67   172.2  796.61
   175.7  794.13  184.61790.3055   206.6  788.97   223.8  789.13  230.68790.3058
     241  792.98   261.6  796.47   268.5  796.57   278.7  795.51   288.9  796.06
   304.7  795.86   329.8  797.07   336.6   798.2   343.4  800.65   360.8  809.07
   367.2  812.34   380.8  821.05   394.4  827.04   404.6  833.14     419  839.29
#Mann= 5 ,-1,0
       0      .1       0     110     .06       0  184.61    .045       0
  230.68     .06       0  234.42      .1       0
Bank Sta=184.61,230.68
XS Rating Curve= 0 ,0
Exp/Cntr(USF)=0,0
Exp/Cntr=0.3,0.1

Type RM Length L Ch R = 1 ,16806   ,296.9,303.5,305.1
XS GIS Cut Line= 6
1622694.67377001459217.0090291651622778.20969218459243.047362924
1622849.81223926459265.3655597571622947.32319909459288.575158998
1623022.54450534459299.2821585831623110.48855518459311.178132176
#Sta/Elev= 30
       0  836.24     5.3  833.65    15.6  830.36    25.9  828.67    36.2  826.02
    65.1  822.84    80.9   822.5    98.2  820.84   109.2  820.77   116.4  819.69
     140  814.45   159.9  808.12   174.5  799.42   180.2   795.5   186.9  790.05
  194.18787.5826   207.2  786.22  239.32787.5826   247.6  790.23   254.4  791.75
   267.8  791.18   294.3  792.02   304.2  794.83   330.7  804.42   363.9  812.81
   377.1  818.29   389.5  825.89     397  829.41   420.1  841.72   427.5   846.3
#Mann= 4 ,-1,0
       0      .1       0  194.18    .045       0  239.32     .06       0
  322.74      .1       0
#XS Ineff= 2 , 0
                          280.14          796.52
Permanent Ineff=
       F       F
Bank Sta=194.18,239.32
XS Rating Curve= 0 ,0
Exp/Cntr(USF)=0,0
Exp/Cntr=0.3,0.1

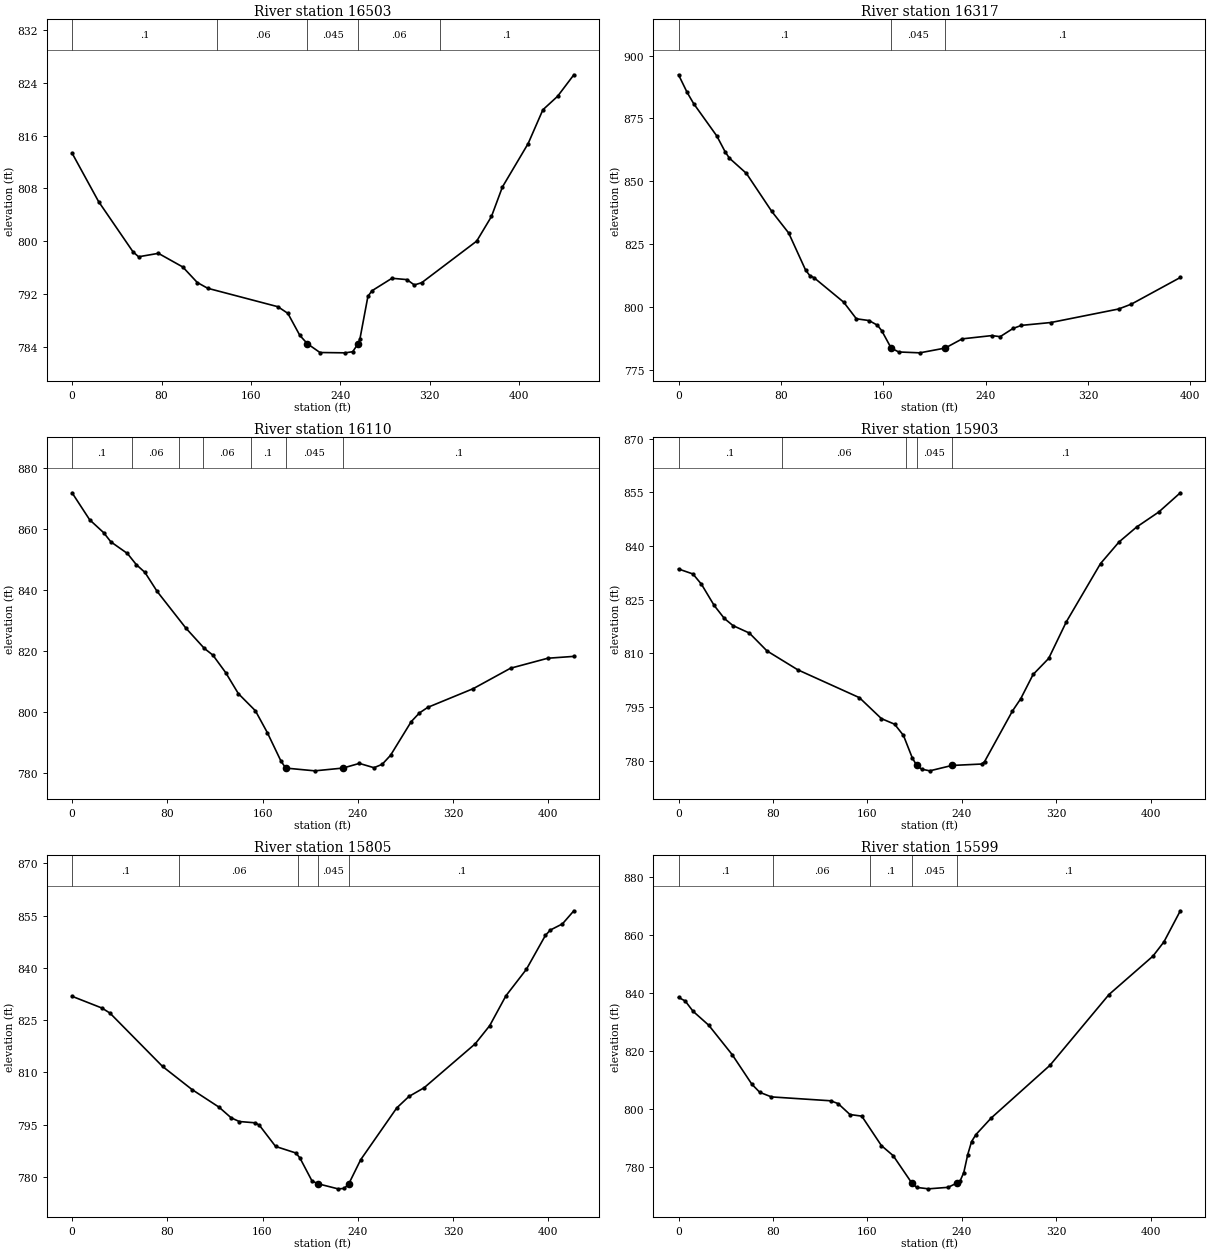
Type RM Length L Ch R = 1 ,16503   ,195.9,185.9,172
XS GIS Cut Line= 4
1622672.88032369459429.8340829891622814.21979076459555.423050508
1622905.80064434459595.5840594171623065.35885523459603.879328745
#Sta/Elev= 30
       0  813.34    23.7  806.02    54.5  798.42    59.5  797.67    77.2  798.19
      99  796.13     112  793.78   121.3  792.91   184.1  790.12     193  789.12
   203.7  785.79  210.42784.5338   221.7   783.2   244.3  783.15     251  783.32
  255.82784.5364   257.5  785.29   264.6  791.68   268.2  792.53   286.1  794.42
   299.5  794.22   306.1  793.41   312.7  793.75   361.9  800.04   375.1  803.76
   384.9  808.22   407.9  814.78   421.1  819.89   434.2  821.92   448.8  825.18
#Mann= 5 ,-1,0
       0      .1       0     130     .06       0  210.42    .045       0
  255.82     .06       0  329.08      .1       0
Bank Sta=210.42,255.82
XS Rating Curve= 0 ,0
Exp/Cntr(USF)=0,0
Exp/Cntr=0.3,0.1

Type RM Length L Ch R = 1 ,16317   ,212,206.5,199
XS GIS Cut Line= 2
1622647.11607044459774.4479923231623036.15150638459725.046667125
#Sta/Elev= 30
       0  892.37     6.7  885.37    11.8  880.91    29.9  868.03    36.5  861.66
    39.8  859.17      53  853.15    72.8  838.05    86.1   829.4    99.3  814.66
   102.6  812.46   105.9  811.62   129.1  801.87     139  795.27   148.9  794.57
   155.5  792.69   158.8  790.54  166.18783.6202   172.1  782.07   188.6  781.72
  208.41783.6221   221.7  787.28   244.8  788.58   251.4  788.16   261.4  791.41
     268  792.65   291.1  793.79     344  799.17     354  801.12   392.2  811.71
#Mann= 3 ,-1,0
       0      .1       0  166.18    .045       0  208.41      .1       0
Bank Sta=166.18,208.41
XS Rating Curve= 0 ,0
Exp/Cntr(USF)=0,0
Exp/Cntr=0.3,0.1

Type RM Length L Ch R = 1 ,16110   ,209.9,207.5,205.2
XS GIS Cut Line= 3
1622686.11778708460031.8995984441622908.78871485 459936.54609063
1623078.01158557459877.268909284
#Sta/Elev= 30
       0  871.89    14.8  863.02    26.5  858.81    32.6  855.78    46.5  851.96
      54  848.29    61.2  845.76    71.5  839.49    95.6  827.47   111.1  820.81
   118.3   818.6     129  812.88   139.7  805.95     154  800.34     164  793.18
   175.4  783.88  179.45781.5284   203.9  780.62  227.54781.5289   241.3  783.06
   253.6  781.65   260.5  782.77   267.5  785.71   284.9  796.78   291.8  799.63
   298.8  801.46     337   807.6   368.3   814.3   399.6  817.58   421.5  818.19
#Mann= 7 ,-1,0
       0      .1       0      50     .06       0      90      .1       0
     110     .06       0     150      .1       0  179.45    .045       0
  227.54      .1       0
Bank Sta=179.45,227.54
XS Rating Curve= 0 ,0
Exp/Cntr(USF)=0,0
Exp/Cntr=0.3,0.1

Type RM Length L Ch R = 1 ,15903   ,93.2,97.3,101.1
XS GIS Cut Line= 6
1622781.37274359460236.7553492491622858.39063418460195.228857502
1622924.40625018460159.6341124181623012.42674342460112.174889758
1623078.44203134460076.5804727521623155.45992193460035.053324834
#Sta/Elev= 30
       0  833.58    12.2  832.19    19.4  829.33    30.2  823.39    38.8  819.77
    46.1  817.78      60  815.69    74.9  810.71     101  805.43   153.2  797.65
   171.8  791.81     183  790.24   190.5  787.11   197.9   780.9   201.7  778.74
   205.9  777.69   212.8  777.22   231.5  778.72   256.7  779.12   259.2   779.8
   282.8  793.92   289.8  797.34   300.3  804.12   313.5  808.61   328.4   818.8
   357.4  835.09   373.1  841.13     388   845.3   406.7  849.48     425  854.86
#Mann= 5 ,-1,0
       0      .1       0    87.5     .06       0   192.5      .1       0
   201.7    .045       0   231.5      .1       0
Bank Sta=201.7,231.5
XS Rating Curve= 0 ,0
Exp/Cntr(USF)=0,0
Exp/Cntr=0.3,0.1

Type RM Length L Ch R = 1 ,15805   ,204.1,206.3,208.1
XS GIS Cut Line= 2
1622796.86383745460279.2677841911623204.42477034460171.202385321
#Sta/Elev= 30
       0  831.86    25.1  828.49    31.8  827.05      76  811.74   100.8   805.1
   123.5  800.04   133.7  796.98   140.5  795.93     154  795.55   157.4  794.85
     171  788.78     188   786.9   191.4  785.49   201.6  778.87  206.58778.0701
   223.4  776.61   228.7  776.72  232.52778.0675   242.5  784.97   272.8  799.83
     283  803.11   295.8  805.62   338.7  818.22   350.9  823.44   364.5  831.99
   381.7   839.6   397.7  849.34   401.8  850.87     412  852.64   421.6   856.4
#Mann= 5 ,-1,0
       0      .1       0      90     .06       0     190      .1       0
  206.58    .045       0  232.52      .1       0
Bank Sta=206.58,232.52
XS Rating Curve= 0 ,0
Exp/Cntr(USF)=0,0
Exp/Cntr=0.3,0.1

Type RM Length L Ch R = 1 ,15599   ,167.8,168.8,170.3
XS GIS Cut Line= 6
1622841.78830518460454.7293227611622928.16575709460440.756253585
1623002.20301059460428.7798995821623100.91967668460412.810771421
1623174.95725825460400.8344174181623261.33438209460386.861676335
#Sta/Elev= 30
       0  838.59     5.6  837.39    12.3  833.82    25.6     829    45.5  818.83
    62.1  808.67    68.8  805.87    78.7  804.29   128.9  802.95   135.2  801.97
   145.2  798.21   155.2  797.66   171.8  787.51   181.8  784.03  197.61774.5715
   201.7  773.09   211.7  772.59   228.3  773.11  235.69774.5715   238.3  775.17
   241.6   778.2   244.9  784.34   248.2  788.91   251.9  791.31   264.8  797.01
   314.6  815.19   364.6   839.6   401.8  852.83   411.1  857.74     425  868.47
#Mann= 5 ,-1,0
       0      .1       0      80     .06       0   162.5      .1       0
  197.61    .045       0  235.69      .1       0
Bank Sta=197.61,235.69
XS Rating Curve= 0 ,0
Exp/Cntr(USF)=0,0
Exp/Cntr=0.3,0.1

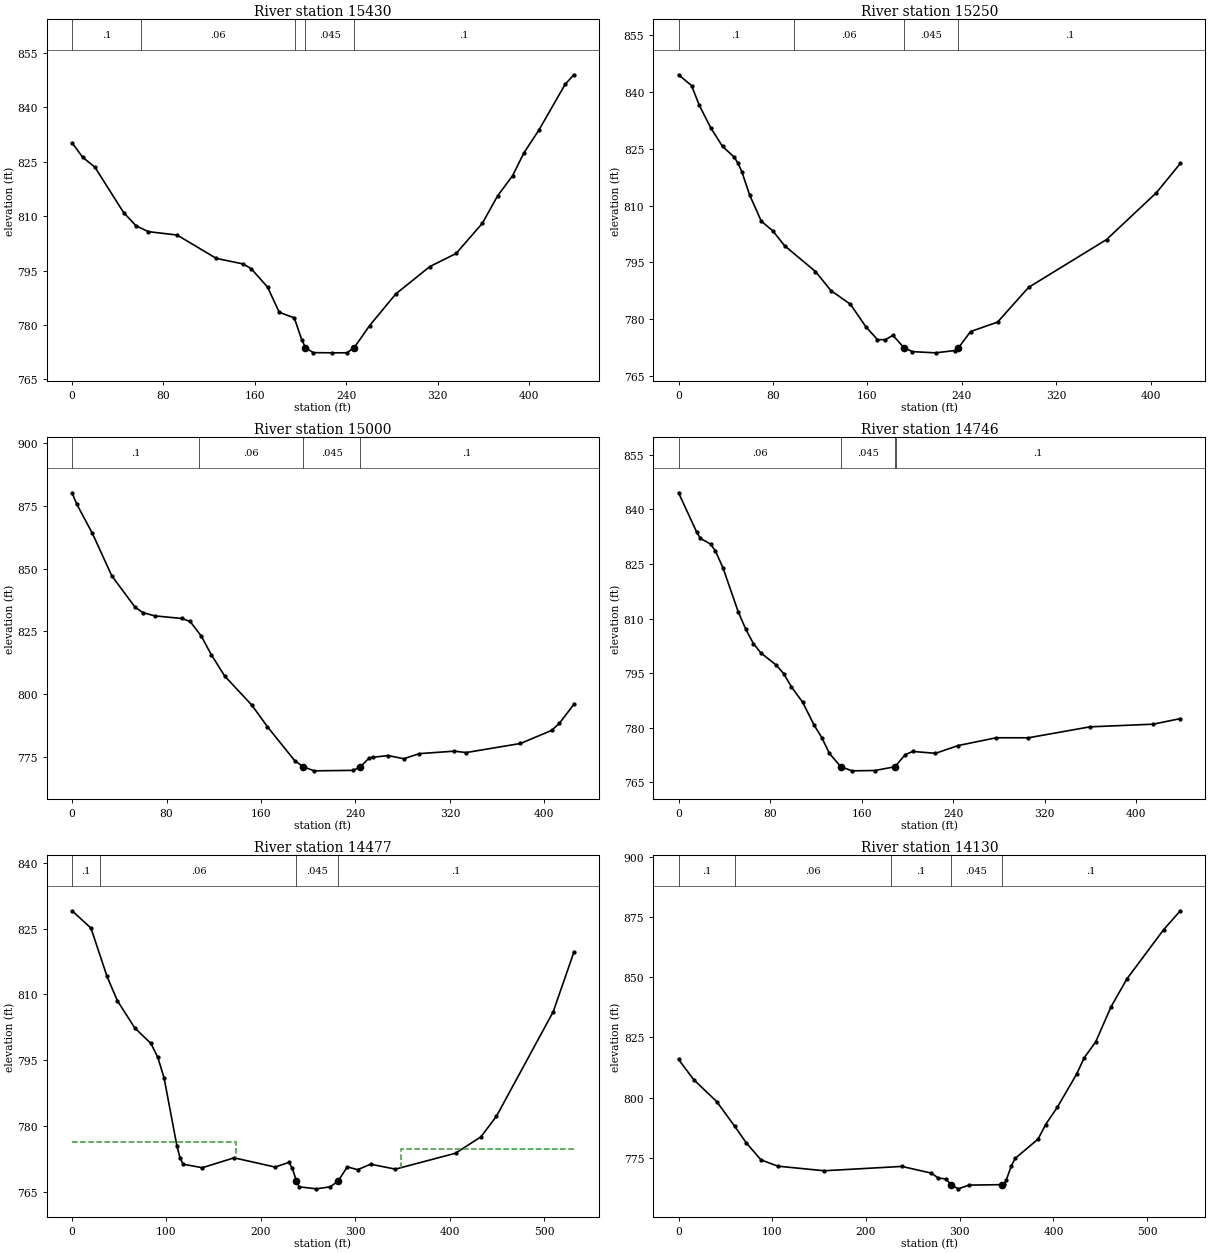
Type RM Length L Ch R = 1 ,15430   ,178.5,179.9,182.1
XS GIS Cut Line= 3
1622858.61549395460521.2142049971623018.14060657460593.257804244
1623281.44280858460569.243271161
#Sta/Elev= 30
       0  830.21     9.2  826.24      20  823.47    45.2  810.95      56  807.33
    66.8  805.72      92  804.78   126.3  798.35   149.6  796.83   156.8  795.54
   171.2  790.43   181.4   783.5   194.6  781.96   201.2  775.87  204.38773.7672
   211.1  772.39   227.5  772.33   240.7  772.35  247.09773.7694   260.5  779.82
   283.5  788.57   313.2  796.08   336.3   799.7   359.3  808.04   372.8  815.67
   385.7  821.09   395.6  827.38   408.7  833.66   431.8  846.31   439.4  848.93
#Mann= 5 ,-1,0
       0      .1       0      60     .06       0  195.04      .1       0
  204.38    .045       0  247.09      .1       0
Bank Sta=204.38,247.09
XS Rating Curve= 0 ,0
Exp/Cntr(USF)=0,0
Exp/Cntr=0.3,0.1

Type RM Length L Ch R = 1 ,15250   ,252.1,250.4,248.2
XS GIS Cut Line= 6
1622878.97739971460770.727721316 1622966.4657418460769.316634906
1623041.45607739460768.1069916461623141.44308213460766.494133977
1623216.43341771460765.2844907321623303.92208788460763.873404322
#Sta/Elev= 30
       0  844.61      11  841.77    17.6  836.53    27.4  830.52    37.3  825.65
    47.1  822.87    50.4   821.2    53.7  818.91    60.2  812.83    70.1   805.9
    79.9  803.33    89.8  799.42     116  792.59   129.1  787.54   145.5  783.96
   158.7  777.98   168.5  774.59   175.1  774.56   181.6  775.73  190.91772.4398
     198  771.41   217.7  771.09   234.1   771.7  237.11772.4388   247.3  776.71
   270.2  779.22   296.5   788.4   362.5  801.04   404.8  813.45     425  821.17
#Mann= 4 ,-1,0
       0      .1       0    97.5     .06       0  190.91    .045       0
  237.11      .1       0
Bank Sta=190.91,237.11
XS Rating Curve= 0 ,0
Exp/Cntr(USF)=0,0
Exp/Cntr=0.3,0.1

Type RM Length L Ch R = 1 ,15000   ,255.3,254,253.2
XS GIS Cut Line= 6
1622899.15531643461038.0093241781622986.22108717461029.302648678
1623060.84889068461021.8400651661623160.35262868461011.889297679
1623234.98043217461004.4263860881623322.04620293460995.720038667
#Sta/Elev= 30
       0  880.17       4  875.62    17.2  864.03    33.6  847.14    53.4  834.59
      60  832.47      70  831.17      93  830.12     100  828.93   109.5  823.07
   117.9  815.71   129.3  807.19   152.3  795.61   165.5  787.01   188.6   773.5
  195.74771.0894   205.1  769.47   238.1  769.66  244.25  771.09   251.3  774.47
   254.6  774.86   267.7  775.56   280.9  774.29   294.1  776.32   323.8  777.31
   333.8  776.75   379.8  780.36   406.2  785.57   412.8  788.43     425  795.95
#Mann= 4 ,-1,0
       0      .1       0   107.5     .06       0  195.74    .045       0
  244.25      .1       0
Bank Sta=195.74,244.25
XS Rating Curve= 0 ,0
Exp/Cntr(USF)=0,0
Exp/Cntr=0.3,0.1

Type RM Length L Ch R = 1 ,14746   ,277.8,269.6,264
XS GIS Cut Line= 3
1622972.82075048461293.353487811 1623252.1423017461252.452737287
1623363.68481971461142.944261441
#Sta/Elev= 30
       0  844.56    15.8   833.8    19.1  832.04    28.1  830.43    32.3  828.55
      39  823.81    52.2  811.81    58.9  806.99    65.5  803.09    72.1  800.52
    85.4  797.21      92  794.82    98.6  791.25   108.6  786.95   118.5  780.72
   125.2  777.31   131.8  772.95  141.88769.2759   151.7  768.15   171.6  768.24
  189.15769.2748   198.1   772.6   204.8  773.48   224.6  772.96   244.5  775.11
   277.7  777.24   305.8  777.23   359.6  780.24   414.8  780.97   438.6   782.5
#Mann= 4 ,-1,0
       0     .06       0  141.88    .045       0  189.15     .06       0
     190      .1       0
Bank Sta=141.88,189.15
XS Rating Curve= 0 ,0
Exp/Cntr(USF)=0,0
Exp/Cntr=0.3,0.1

Type RM Length L Ch R = 1 ,14477   ,295.8,346.2,366
XS GIS Cut Line= 4
1622978.72735842461521.1757816411623148.61109891461560.693363761
1623339.59806449461469.0419410811623482.43598923461443.345583998
#Sta/Elev= 30
       0  829.04      20  825.09      37   814.1    47.9  808.57    66.4  802.33
    83.5   798.8    90.8  795.64    97.5  790.88     111  775.48   114.4  772.68
   117.7  771.28   137.9  770.47   171.6  772.73   215.1  770.62   229.6  771.69
   233.3  770.32  237.67767.3601   240.5  766.12   258.7  765.66   273.3  766.12
  281.46 767.358   291.5  770.68   302.4  770.02   316.1  771.28   342.4  770.15
   406.1  773.78     433  777.52   449.4   782.2   509.5  806.01   531.4  819.59
#Mann= 4 ,-1,0
       0      .1       0      30     .06       0  237.67    .045       0
  281.46      .1       0
#XS Ineff= 2 , 0
          173.72  776.33  348.74          774.66
Permanent Ineff=
       F       F
Bank Sta=237.67,281.46
XS Rating Curve= 0 ,0
Exp/Cntr(USF)=0,0
Exp/Cntr=0.3,0.1

Type RM Length L Ch R = 1 ,14130   ,322.1,330.4,335.8
XS GIS Cut Line= 3
1622960.21863707461574.0105078351623125.98833511461729.082669918
1623310.69518563461975.927594218
#Sta/Elev= 30
       0  815.89    16.1  807.53    40.7   798.4      60  788.08    72.1  781.33
      88  774.16     106  771.56   155.4  769.66   238.3  771.46   269.8  768.66
   277.1  766.63   285.3  766.26  290.46763.8864   298.5  762.15   309.8   763.7
  344.75763.8843   347.2  764.16   349.5  765.64   354.9  771.54     359  774.76
   383.6  782.83   391.6  788.86   404.1  796.03   424.6  809.75   432.8  816.58
   445.1  823.26   461.4  837.74   478.4  849.38   517.6  869.82   535.3  877.61
#Mann= 5 ,-1,0
       0      .1       0      60     .06       0     227      .1       0
  290.46    .045       0  344.75      .1       0
Bank Sta=290.46,344.75
XS Rating Curve= 0 ,0
Exp/Cntr(USF)=0,0
Exp/Cntr=0.3,0.1

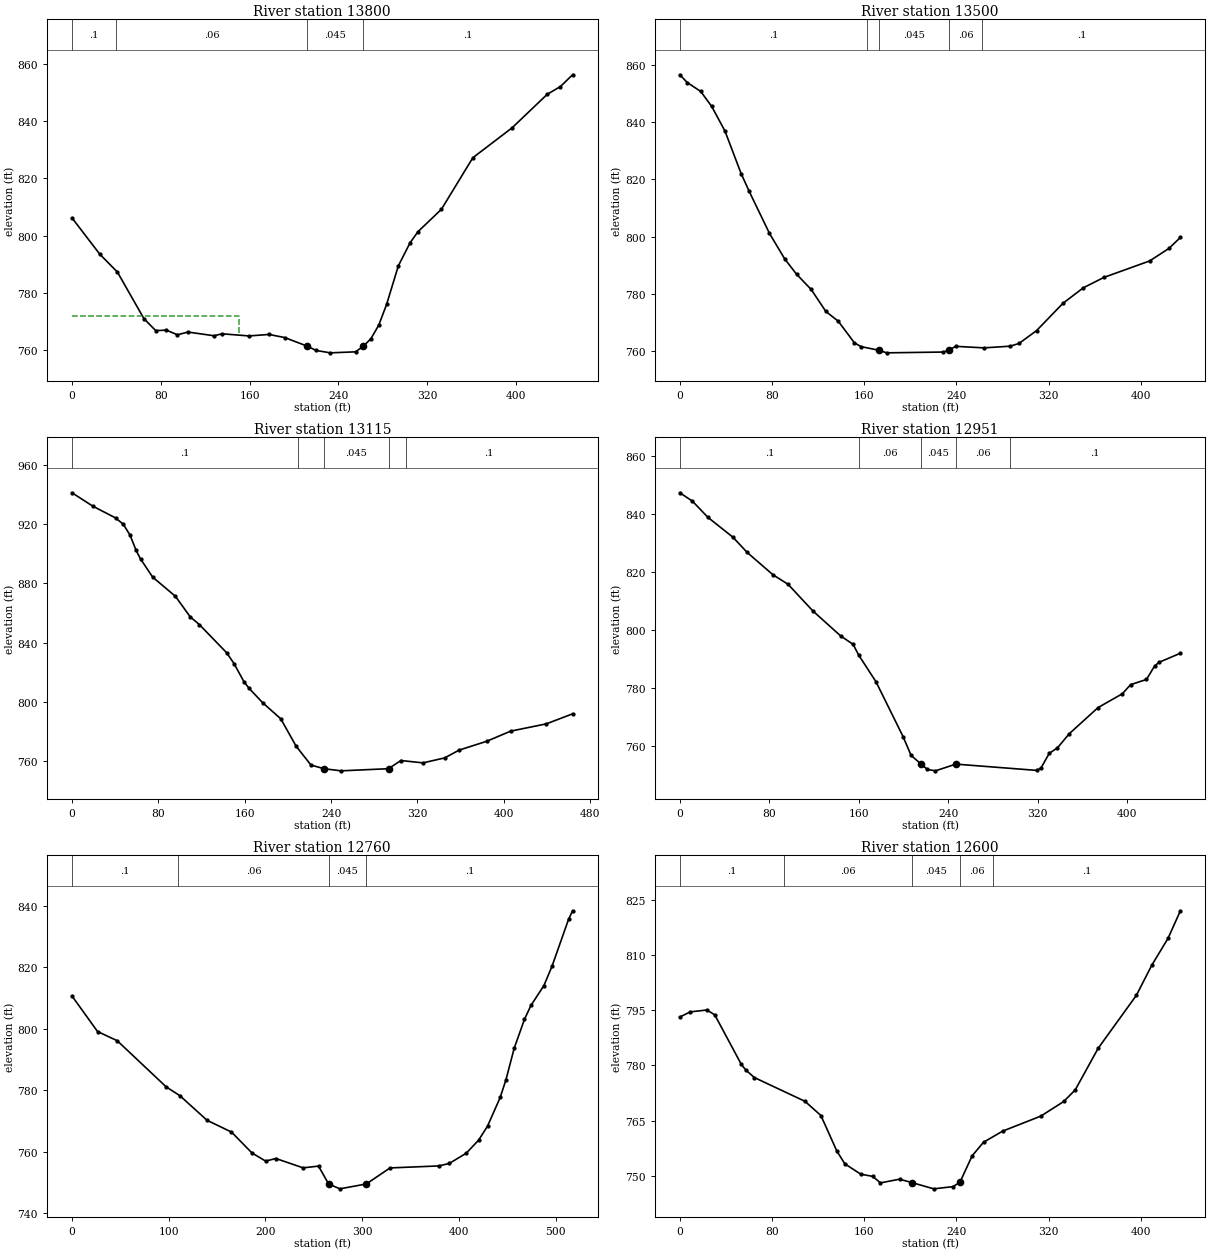
Type RM Length L Ch R = 1 ,13800   ,300.1,300,300.3
XS GIS Cut Line= 6
1622800.84727187461762.0412836751622856.95362918461860.521458671
 1622884.6241775461930.2303087561622921.51846068462023.175660923
1622949.18900901462092.8845110091622981.47142476462174.211776167
#Sta/Elev= 30
       0  806.19    24.9  793.58    40.9  787.28    64.8  771.01    75.4  766.85
      85  767.01      95  765.39   104.3  766.35     128  765.05   135.1  765.74
   159.4  764.99   177.4  765.51   191.5  764.43  212.01 761.403   219.8  759.92
   232.7  759.09   255.4  759.44  262.38761.4051   269.2  764.02   276.3   768.8
   283.3  775.97   293.9  789.46   304.5  797.54   311.6  801.39   332.7  809.21
     361  827.21   396.3  837.63     428  849.35   439.9  852.06   450.8  856.16
#Mann= 4 ,-1,0
       0      .1       0      40     .06       0  212.01    .045       0
  262.38      .1       0
#XS Ineff= 2 , 0
          150.18  771.84
Permanent Ineff=
       F       F
Bank Sta=212.01,262.38
XS Rating Curve= 0 ,0
Exp/Cntr(USF)=0,0
Exp/Cntr=0.3,0.1

Type RM Length L Ch R = 1 ,13500   ,406.1,385.5,352.7
XS GIS Cut Line= 6
1622546.45293784461883.4981187581622577.68056567461965.235816166
1622604.44691634462035.2970277521622640.13582134 462128.71153909
1622666.90217201462198.7727506761622725.76557204462275.745659773
#Sta/Elev= 30
       0  856.55     6.5  853.83    18.1  850.73    27.6  845.53    39.2  836.85
    53.2  821.99    60.2  815.78    77.8  801.08    91.1  792.11   101.3  786.81
     114  781.47   126.7  773.81   137.5  770.37   151.5  762.82   157.2   761.5
  172.61 760.228   179.6  759.32   228.8   759.6  233.33760.2296   239.4  761.59
   263.9  761.06   286.8  761.65   294.4  762.61   309.6   767.1   332.5  776.64
   350.1  782.05     368  785.69   407.7  791.45   424.5  795.84   434.4  799.67
#Mann= 5 ,-1,0
       0      .1       0   162.5     .06       0  172.61    .045       0
  233.33     .06       0   262.5      .1       0
Bank Sta=172.61,233.33
XS Rating Curve= 0 ,0
Exp/Cntr(USF)=0,0
Exp/Cntr=0.3,0.1

Type RM Length L Ch R = 1 ,13115   ,161.6,163.4,170.5
XS GIS Cut Line= 4
1622210.26094638462159.0984922971622334.43230828462315.189945459
1622442.11652409462352.3552942771622589.11620428462384.375127456
#Sta/Elev= 30
       0  941.16    19.4  932.07    40.3   924.2    47.5  919.91    53.7  912.71
    59.3  902.43    63.5  896.49    74.7  884.25    95.8  871.28   109.6  857.35
     118  852.19   143.3  833.16   150.2  825.76   159.5  813.36   164.1  809.13
   176.7   799.4   193.5  788.52   207.6  770.14   221.4  757.35  233.47754.8865
   249.2  753.44  293.31754.8865   304.7  760.42   325.2  758.81   345.3  762.17
   358.7  767.44   384.4  773.43   406.4  780.24   439.5  785.15   463.8  791.92
#Mann= 5 ,-1,0
       0      .1       0  209.46     .06       0  233.47    .045       0
  293.31     .06       0  309.46      .1       0
Bank Sta=233.47,293.31
XS Rating Curve= 0 ,0
Exp/Cntr(USF)=0,0
Exp/Cntr=0.3,0.1

Type RM Length L Ch R = 1 ,12951   ,191.2,191.3,192.2
XS GIS Cut Line= 5
1622147.45555838462324.8923707151622273.20574757462460.510482899
1622363.49132814462503.5041633161622431.27498523462535.615975729
1622510.27285873462573.234338811
#Sta/Elev= 30
       0  847.35    11.2  844.48    25.1  838.87    47.5     832    60.2  826.76
    83.3  819.03    96.7  815.78   119.1  806.49   143.8  797.93   154.9  795.03
     160  791.24   175.3  782.15   199.5  763.22   206.7  756.72   215.2  753.85
   221.3  751.86   228.5  751.38   246.7   753.7   319.4  751.52     323  752.49
   330.2  757.43   337.5  759.31   348.1   764.2   373.8  773.21   395.6     778
   402.9  781.13   417.1  782.92   424.4   787.6   428.3  788.83   447.4  791.97
#Mann= 5 ,-1,0
       0      .1       0     160     .06       0   215.2    .045       0
   246.7     .06       0  294.95      .1       0
Bank Sta=215.2,246.7
XS Rating Curve= 0 ,0
Exp/Cntr(USF)=0,0
Exp/Cntr=0.3,0.1

Type RM Length L Ch R = 1 ,12760   ,138.6,159.8,177.3
XS GIS Cut Line= 4
1622121.92274966462423.827118927 1622210.2895607 462639.23176293
1622309.29137924462685.9629007591622423.73397079462818.762315747
#Sta/Elev= 30
       0  810.59    26.4  799.04    46.7  796.07    97.4  781.05   111.5   778.2
   139.7  770.18   164.9  766.37     186   759.6   200.2  756.93   210.8  757.77
     239  754.73   254.9   755.3  265.36 749.493     277  747.91  304.32749.4951
   328.9  754.71   379.4  755.36   390.1  756.16   407.6  759.48   420.4  763.71
   429.7  768.31   442.8  777.64   448.7  783.35   457.3  793.66   467.9  803.03
   474.6  807.54     488     814   496.3  820.22   513.4  835.46   517.6  838.29
#Mann= 4 ,-1,0
       0      .1       0     110     .06       0  265.36    .045       0
  304.32      .1       0
Bank Sta=265.36,304.32
XS Rating Curve= 0 ,0
Exp/Cntr(USF)=0,0
Exp/Cntr=0.3,0.1

Type RM Length L Ch R = 1 ,12600   ,91.3,92.8,95.3
XS GIS Cut Line= 6
  1622048.549078462529.4915774171622094.89642626 462613.13773559
 1622118.5469695462685.5204648381622132.68900159462784.515345588
1622143.29560767462858.7615881711622155.66992676462945.382149845
#Sta/Elev= 30
       0  793.17       9  794.57    23.5  795.08    30.3  793.76    53.4  780.25
    57.3  778.71    64.7  776.69   108.6  770.22   122.4  766.36   136.2   756.7
   143.1  753.23   156.9   750.4   167.3  749.79   174.1  748.03   190.6  749.02
   201.4   748.1   220.3   746.4     237     747  243.04748.1796   253.6  755.39
   263.5  759.09   280.1  762.11   313.3  766.21   333.1  770.18   343.1  773.35
     363  784.68   396.1  799.07   409.4  807.22   423.6  814.61   434.3  822.09
#Mann= 5 ,-1,0
       0      .1       0      90     .06       0   201.4    .045       0
  243.04     .06       0  271.78      .1       0
Bank Sta=201.4,243.04
XS Rating Curve= 0 ,0
Exp/Cntr(USF)=0,0
Exp/Cntr=0.3,0.1

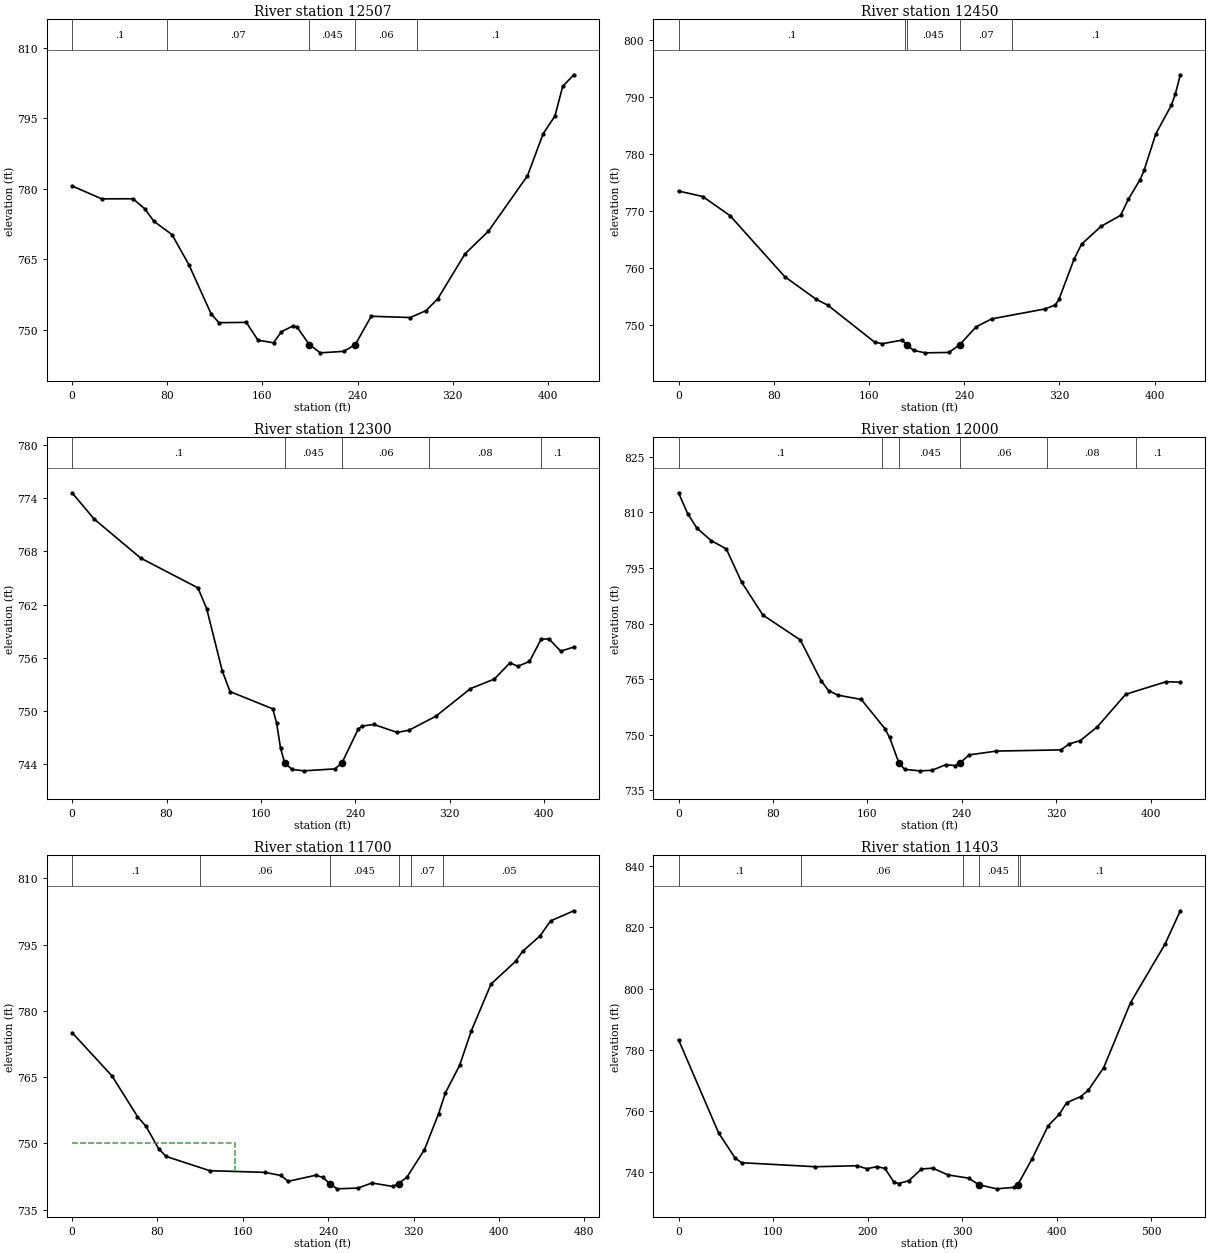
Type RM Length L Ch R = 1 ,12507   ,57.1,56.9,56.9
XS GIS Cut Line= 2
1622026.07743375462531.6696139461622040.74345216462953.124669546
#Sta/Elev= 30
       0  780.59    24.9  777.84    51.2  777.86      61  775.74    68.9  773.04
      84  770.23    98.1  763.87   116.8  753.41   123.4   751.5   146.4  751.57
   156.2  747.79   169.3  747.22   175.9  749.57   185.8  750.84     189  750.59
  199.36746.8476   208.7  745.09   228.4  745.41     238  746.84   251.4  752.87
   284.2   752.6   297.4  754.06   307.2  756.54   330.2  766.13   349.9  770.96
   382.7  782.74   395.9   791.7   405.8  795.45   412.3  801.76   421.7  804.23
#Mann= 5 ,-1,0
       0      .1       0      80     .07       0  199.36    .045       0
     238     .06       0     290      .1       0
Bank Sta=199.36,238
XS Rating Curve= 0 ,0
Exp/Cntr(USF)=0,0
Exp/Cntr=0.3,0.1

Type RM Length L Ch R = 1 ,12450   ,152.1,150.4,149.6
XS GIS Cut Line= 2
1621969.34309934462536.3009881831621984.00911776462957.756043783
#Sta/Elev= 30
       0   773.5    20.3  772.54    43.2   769.2    89.2  758.49   115.5  754.54
   125.3   753.5   164.7  747.01   171.3  746.72   187.7  747.35  192.16746.5164
   197.5  745.54   207.4  745.12   227.1  745.19  236.21746.5157   250.1  749.69
   263.2  751.08     308  752.82   316.6   753.5   319.7   754.5   332.4  761.54
   338.7  764.18   355.1  767.31   371.5  769.23   378.1  772.09   387.9   775.5
   391.2  777.11   401.1  783.53   414.2  788.57   417.5  790.52   421.7  793.89
#Mann= 5 ,-1,0
       0      .1       0     190     .07       0  192.16    .045       0
  236.21     .07       0     280      .1       0
Bank Sta=192.16,236.21
XS Rating Curve= 0 ,0
Exp/Cntr(USF)=0,0
Exp/Cntr=0.3,0.1

Type RM Length L Ch R = 1 ,12300   ,324.9,300,281.1
XS GIS Cut Line= 6
1621809.38026501462544.6099855011621816.49967334462631.819784835
1621822.60169525462706.5712757561621830.73816192462806.239711583
1621836.84018384462880.9912025031621848.13248409462967.860451341
#Sta/Elev= 30
       0  774.58    18.6  771.64    58.1  767.23   106.6  763.88     114  761.55
   127.2  754.55   133.8   752.2     170  750.26   173.3  748.64   176.6  745.85
  180.11744.1635   186.4  743.44   196.3  743.28   222.7   743.5  228.58744.1629
   242.4  747.97   245.7  748.32   255.6   748.5   275.3  747.61   285.2  747.84
   308.2  749.43   337.5  752.53   357.7  753.61     371  755.44   377.6  755.05
   387.5  755.59   397.4  758.11     404  758.13     414  756.75   425.1  757.22
#Mann= 5 ,-1,0
       0      .1       0  180.11    .045       0  228.58     .06       0
   302.5     .08       0   397.5      .1       0
Bank Sta=180.11,228.58
XS Rating Curve= 0 ,0
Exp/Cntr(USF)=0,0
Exp/Cntr=0.3,0.1

Type RM Length L Ch R = 1 ,12000   ,312.3,299.8,275.9
XS GIS Cut Line= 6
1621420.35906142462788.8129091711621492.53345776462838.280986086
1621554.39717917462880.6824760881621636.88225043 462937.21713993
1621699.46873942462978.5644981711621775.00894268463023.121823758
#Sta/Elev= 30
       0  815.24     7.7  809.64    15.7  805.66    27.6  802.37    40.5   800.1
    53.4  791.19    71.4   782.3   103.2  775.57   120.7  764.63   127.1  761.93
   134.9   760.7   154.9  759.53   174.8  751.68   178.8  749.31  186.64742.5085
   191.5  740.69   204.3  740.29   214.6  740.42   226.5  741.95   234.5  741.71
  238.69 742.507   246.4  744.59   269.4  745.62   323.9  745.93     331  747.53
   340.5  748.46   354.9  752.16   378.9  760.92   413.2  764.32   425.2  764.19
#Mann= 6 ,-1,0
       0      .1       0   172.5     .06       0  186.64    .045       0
  238.69     .06       0   312.5     .08       0  387.51      .1       0
Bank Sta=186.64,238.69
XS Rating Curve= 0 ,0
Exp/Cntr(USF)=0,0
Exp/Cntr=0.3,0.1

Type RM Length L Ch R = 1 ,11700   ,272.3,297.3,324.4
XS GIS Cut Line= 5
1621284.40693161 463084.899214911621441.53201696463193.067021921
1621558.42374593463189.910860255 1621633.3865225463187.544067085
1621720.84271242463184.782589674
#Sta/Elev= 30
       0  775.09    37.4   765.3    61.3   756.1    69.3  753.87      81  748.85
    88.1  747.07     129  743.84   180.8  743.46   195.7  742.75   202.5  741.43
   228.5  742.82     235   742.3  241.65740.9016   248.2  739.73   267.9  739.91
     281  741.06   300.7  740.26  305.89740.9013   313.8  742.37   330.2  748.61
   343.4  756.71   349.9   761.5   363.1  767.66   374.2  775.55   392.6   786.1
   415.6  791.23   422.1  793.48   438.5  796.99   448.4  800.39   470.2  802.68
#Mann= 6 ,-1,0
       0      .1       0     120     .06       0  241.65    .045       0
  305.89     .06       0  317.69     .07       0  347.69     .05       0
#XS Ineff= 2 , 0
          152.35  750.11
Permanent Ineff=
       F       F
Bank Sta=241.65,305.89
XS Rating Curve= 0 ,0
Exp/Cntr(USF)=0,0
Exp/Cntr=0.3,0.1

Type RM Length L Ch R = 1 ,11403   ,318.6,306,290.7
XS GIS Cut Line= 4
1621157.05558577463275.3221541211621411.69077167463417.033437505
1621454.53614899463495.7246751711621577.66435143463585.262892241
#Sta/Elev= 30
       0  783.28    42.3  752.88    59.8  744.61    66.7  743.07   144.9  741.75
   188.9  742.08   199.2  741.09   209.8  741.77   218.3  741.22   228.1  736.62
     233  736.26   243.8   737.2     257  741.01   268.9  741.29   285.2  739.06
   306.8  738.03   317.9  735.84   336.6  734.52   355.2  735.01     359  735.91
     374   744.3   391.1  755.17   402.8  758.87   410.7  762.73   425.5  764.67
   433.6   766.8   449.8  774.15   478.2   795.4   514.7  814.56   530.9  825.46
#Mann= 6 ,-1,0
       0      .1       0     130     .06       0  301.41      .1       0
   317.9    .045       0     359     .06       0  361.41      .1       0
Bank Sta=317.9,359
XS Rating Curve= 0 ,0
Exp/Cntr(USF)=0,0
Exp/Cntr=0.3,0.1