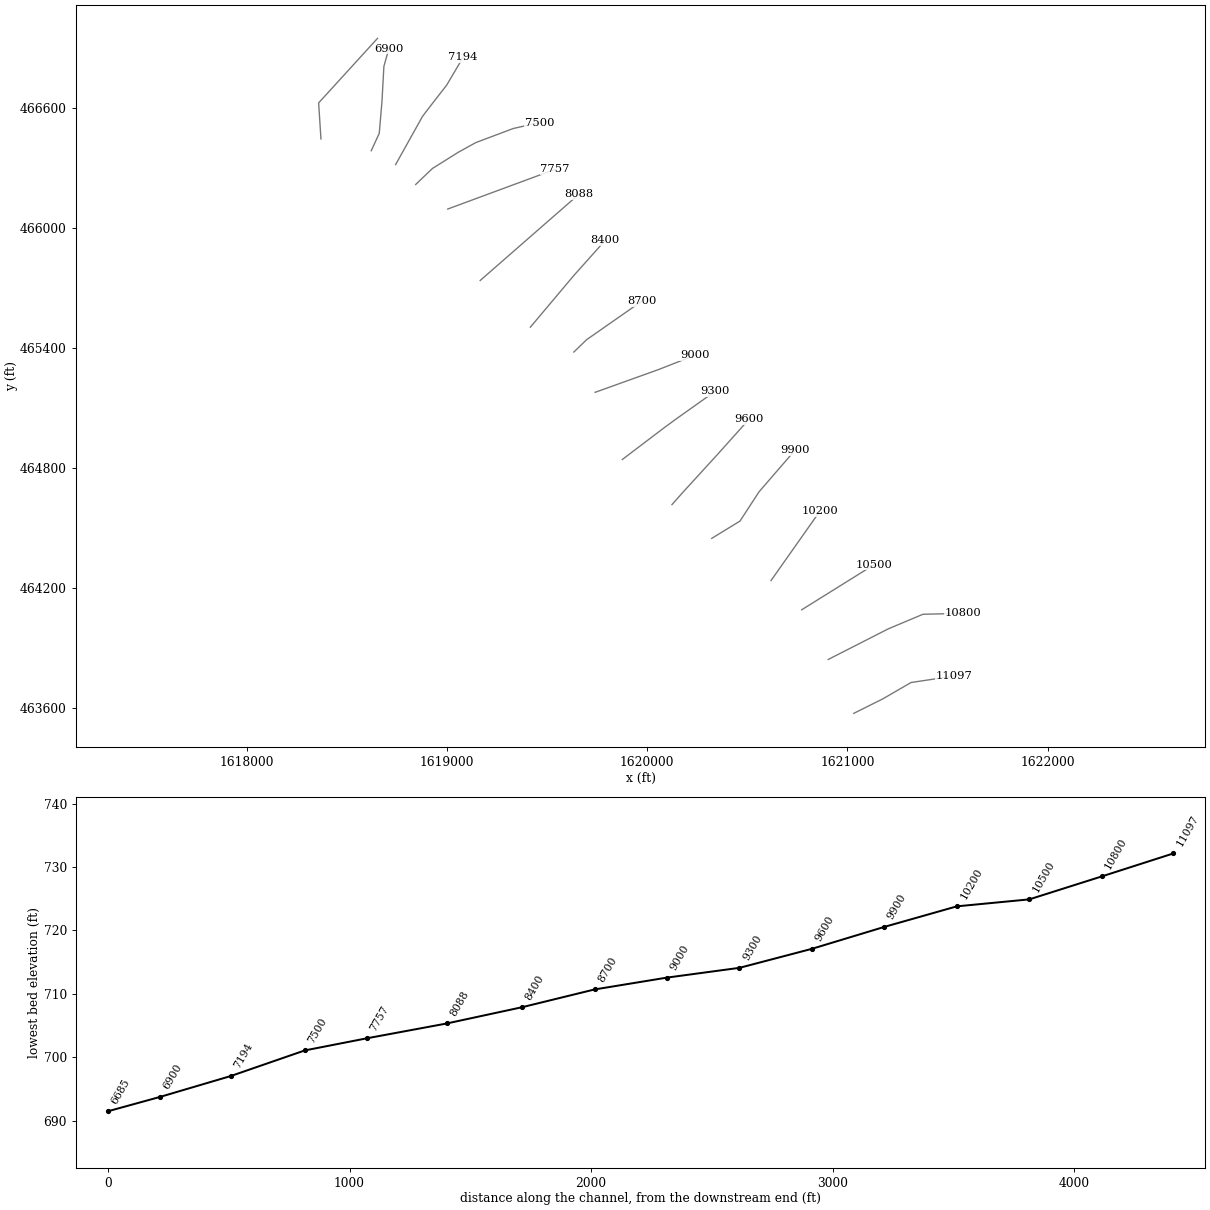
HEC-RAS study WhtstneCrk.prj: WhtstneCrk

--- WhtstneCrk.g01 (geometry) --- (continued)

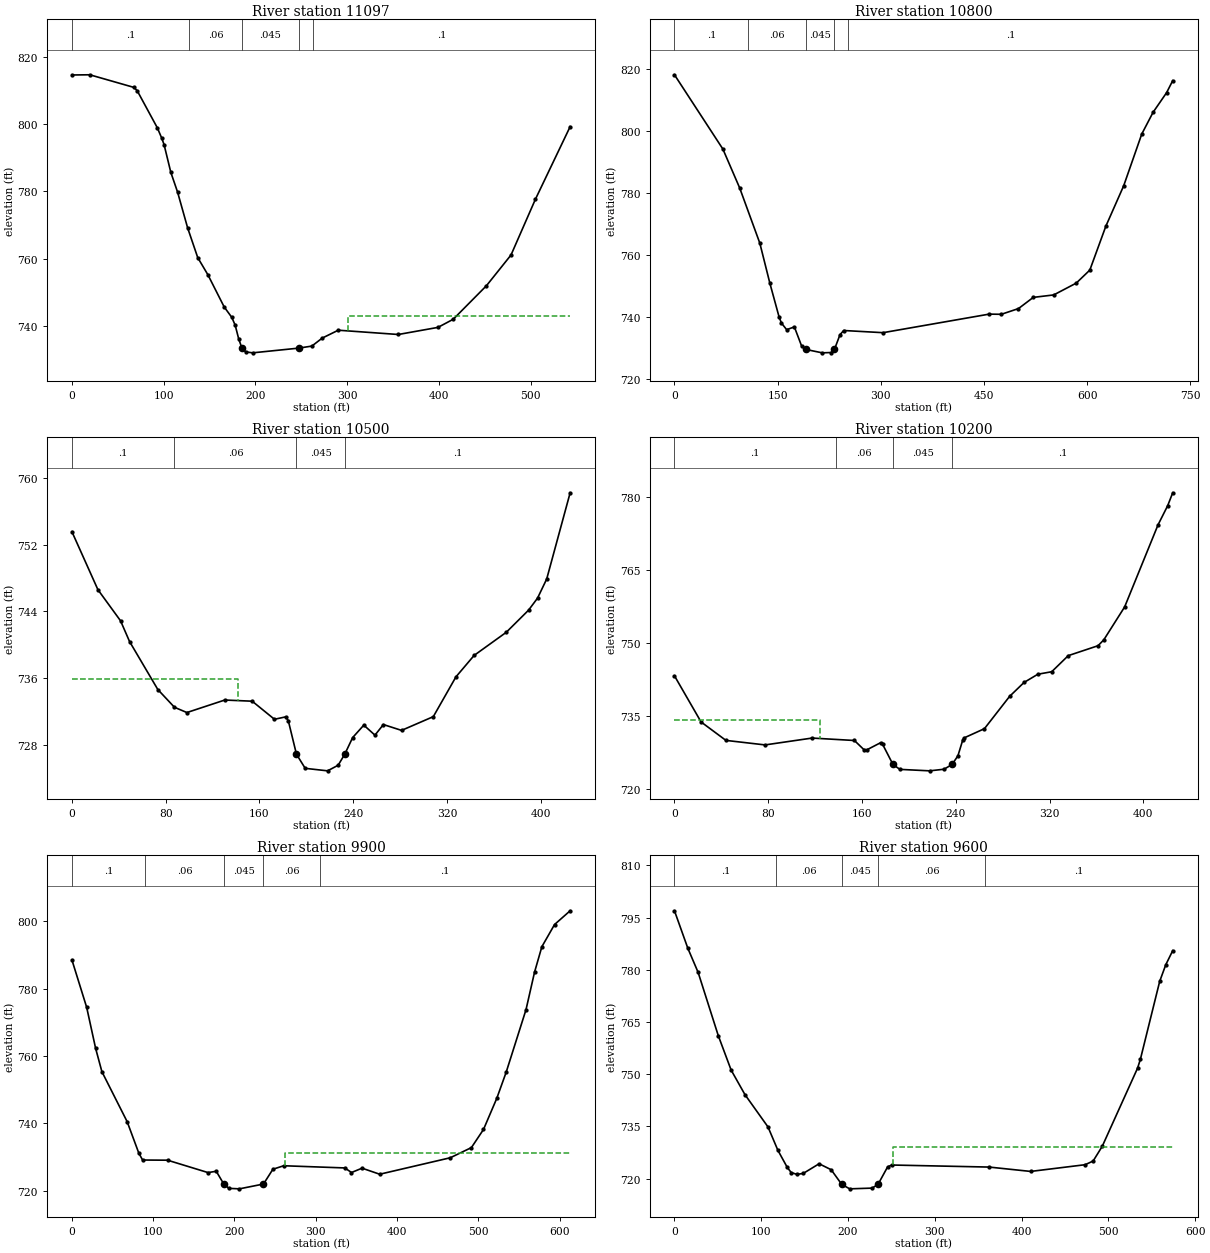
Type RM Length L Ch R = 1 ,11097   ,298.6,296.9,295
XS GIS Cut Line= 5
1621031.81849992463571.4317507591621110.08113867463610.562906086
1621177.16302551  463644.1038495 1621318.3935927463725.895304912
1621533.12918058463757.966858438
#Sta/Elev= 30
       0  814.54    19.5   814.6    67.4  810.87    71.1   809.9    93.1  798.86
    97.9  795.79   100.4  793.91   107.8  785.64   115.1  779.84   126.1  769.19
   137.1  760.38   148.1  755.32   165.9  745.75   174.2  742.66   177.9  740.33
   181.7   736.3  185.24733.5296   189.3  732.42   196.9  732.14  246.92733.5332
   261.4  734.14   272.7  736.51   290.2  738.85   355.6  737.58   398.8  739.69
   415.4  742.09   451.6  752.04   478.4  761.16   504.9  777.65   542.8  799.22
#Mann= 5 ,-1,0
       0      .1       0   127.5     .06       0  185.24    .045       0
  246.92     .06       0   262.5      .1       0
#XS Ineff= 2 , 0
                          301.08          743.18
Permanent Ineff=
       F       F
Bank Sta=185.24,246.92
XS Rating Curve= 0 ,0
Exp/Cntr(USF)=0,0
Exp/Cntr=0.3,0.1

Type RM Length L Ch R = 1 ,10800   ,298.2,300,301.7
XS GIS Cut Line= 6
1620904.02479225463840.8583772631620981.96886209463880.619452596
1621048.77843976463914.700093091 1621204.6669075463994.222243756
1621377.44732955464066.9460496681621576.73404062464071.631029193
#Sta/Elev= 30
       0  818.02    70.4   794.1    94.8  781.59   124.1  763.81   138.7  750.91
   152.2  739.97   155.5   738.1   163.1  735.97   174.3  736.86     185  730.61
  191.12729.5985   214.8  728.51   227.7  728.61  232.56729.6002   240.6  734.34
     246   735.7   303.2     735   457.4  740.97   475.2  740.92   500.1  742.76
   521.6  746.36   551.3  747.15   584.1  750.96   603.8  755.15   627.1  769.28
     653  782.27   679.3  798.94   695.7  805.92   715.4  812.26   724.3  816.12
#Mann= 5 ,-1,0
       0      .1       0   107.5     .06       0  191.12    .045       0
  232.56     .06       0   252.5      .1       0
Bank Sta=191.12,232.56
XS Rating Curve= 0 ,0
Exp/Cntr(USF)=0,0
Exp/Cntr=0.3,0.1

Type RM Length L Ch R = 1 ,10500   ,290.6,300,308.4
XS GIS Cut Line= 6
1620771.45222276464089.2479723391620845.69682492464135.551029339
1620909.33514909464175.2395982591620994.18635733464228.157471418
1621057.82468151464267.8457122591621132.06961176464314.148769259
#Sta/Elev= 30
       0  753.57    22.2  746.61    41.5  742.88    49.2  740.39    73.3  734.64
    87.5  732.51    98.1  731.88   130.4  733.38   153.8  733.24   172.8  731.07
   182.3  731.36   184.6   730.9  191.54726.8865     199  725.19   218.1  724.89
   227.1  725.56  232.75726.8858   239.5  728.88     249  730.37   258.5  729.17
   265.7  730.44   281.2  729.74   308.3  731.39   327.6  736.16   343.1  738.73
   370.5   741.5   389.5  744.15   397.2   745.6     405  747.89     425  758.23
#Mann= 4 ,-1,0
       0      .1       0    87.5     .06       0  191.54    .045       0
  232.75      .1       0
#XS Ineff= 2 , 0
          141.88  735.87
Permanent Ineff=
       F       F
Bank Sta=191.54,232.75
XS Rating Curve= 0 ,0
Exp/Cntr(USF)=0,0
Exp/Cntr=0.3,0.1

Type RM Length L Ch R = 1 ,10200   ,299,300,300.9
XS GIS Cut Line= 6
1620618.35738459464235.4839003381620668.73818934464307.024439678
1620711.92150192464368.3445270061620769.49947076464450.105190262
1620812.68278334 464511.42560567   1620863.06326464582.966145009
#Sta/Elev= 30
       0  743.33    22.7  733.84    43.9  730.05    77.3  729.12   117.4  730.53
   153.5  730.03   161.5  728.17     164   728.1   175.8  729.57   177.6  729.22
  186.39725.0951   192.3  724.09   217.7  723.79   229.9  724.12   236.8 725.095
   241.8  726.89   245.8  730.05   247.3  730.59   264.4  732.46   285.9  739.11
   298.2  741.97     310  743.66   321.8  744.17   335.9  747.48   361.3  749.52
   366.2  750.72     384   757.5   412.5  774.39   420.7  778.31     425  780.97
#Mann= 4 ,-1,0
       0      .1       0   137.5     .06       0  186.39    .045       0
   236.8      .1       0
#XS Ineff= 2 , 0
          124.55  734.18
Permanent Ineff=
       F       F
Bank Sta=186.39,236.8
XS Rating Curve= 0 ,0
Exp/Cntr(USF)=0,0
Exp/Cntr=0.3,0.1

Type RM Length L Ch R = 1 ,9900    ,304.6,300,296.6
XS GIS Cut Line= 5
1620322.47842171464446.6219192771620463.38951868464533.012176678
1620517.93468517464616.8259854171620558.84405218464679.686752096
1620737.16181334464885.967352062
#Sta/Elev= 30
       0  788.59    18.2  774.46    29.2  762.28    36.9  755.37      68   740.5
    82.3  731.18      87  729.11   117.7  729.06   167.5  725.38   177.6  725.77
  186.88721.9758   193.2  720.69   206.1  720.55  235.71721.9779   247.3  726.37
   260.6  727.41   335.8  726.76     344   725.4     357  726.69   378.7  724.89
   465.5  729.78   491.5   732.8   506.4  738.19   522.7  747.41   534.3   755.2
   558.7  773.78   569.2  784.92   578.2  792.48   593.8  799.07     613  803.16
#Mann= 5 ,-1,0
       0      .1       0      90     .06       0  186.88    .045       0
  235.71     .06       0  305.28      .1       0
#XS Ineff= 2 , 0
                          262.31          731.17
Permanent Ineff=
       F       F
Bank Sta=186.88,235.71
XS Rating Curve= 0 ,0
Exp/Cntr(USF)=0,0
Exp/Cntr=0.3,0.1

Type RM Length L Ch R = 1 ,9600    ,302.8,300,295.1
XS GIS Cut Line= 6
1620123.50634018464615.2492169291620181.64795618464680.649676666
1620232.23446918464736.0209570081620299.68315317464809.849877596
1620350.26933809464865.2214860021620508.11217562465041.588389878
#Sta/Elev= 30
       0  796.94    15.4  786.18    27.3  779.23    50.5  761.08    65.3   751.2
    81.2  744.16   107.8  734.86   119.2  728.15     130  723.24   134.5  721.78
   141.1  721.24   148.4  721.52   166.7  724.29   180.6  722.58  192.68718.3986
   201.9  717.09   227.8   717.3  234.66 718.398   245.6  723.38   250.3  723.93
   362.7  723.34   410.5  722.09   473.3  724.02   482.5  725.08     493  729.31
   533.7  751.75     537  754.35   559.2  776.68   566.2  781.44   574.2  785.49
#Mann= 5 ,-1,0
       0      .1       0  117.51     .06       0  192.68    .045       0
  234.66     .06       0  357.51      .1       0
#XS Ineff= 2 , 0
                          252.13          729.05
Permanent Ineff=
       F       F
Bank Sta=192.68,234.66
XS Rating Curve= 0 ,0
Exp/Cntr(USF)=0,0
Exp/Cntr=0.3,0.1

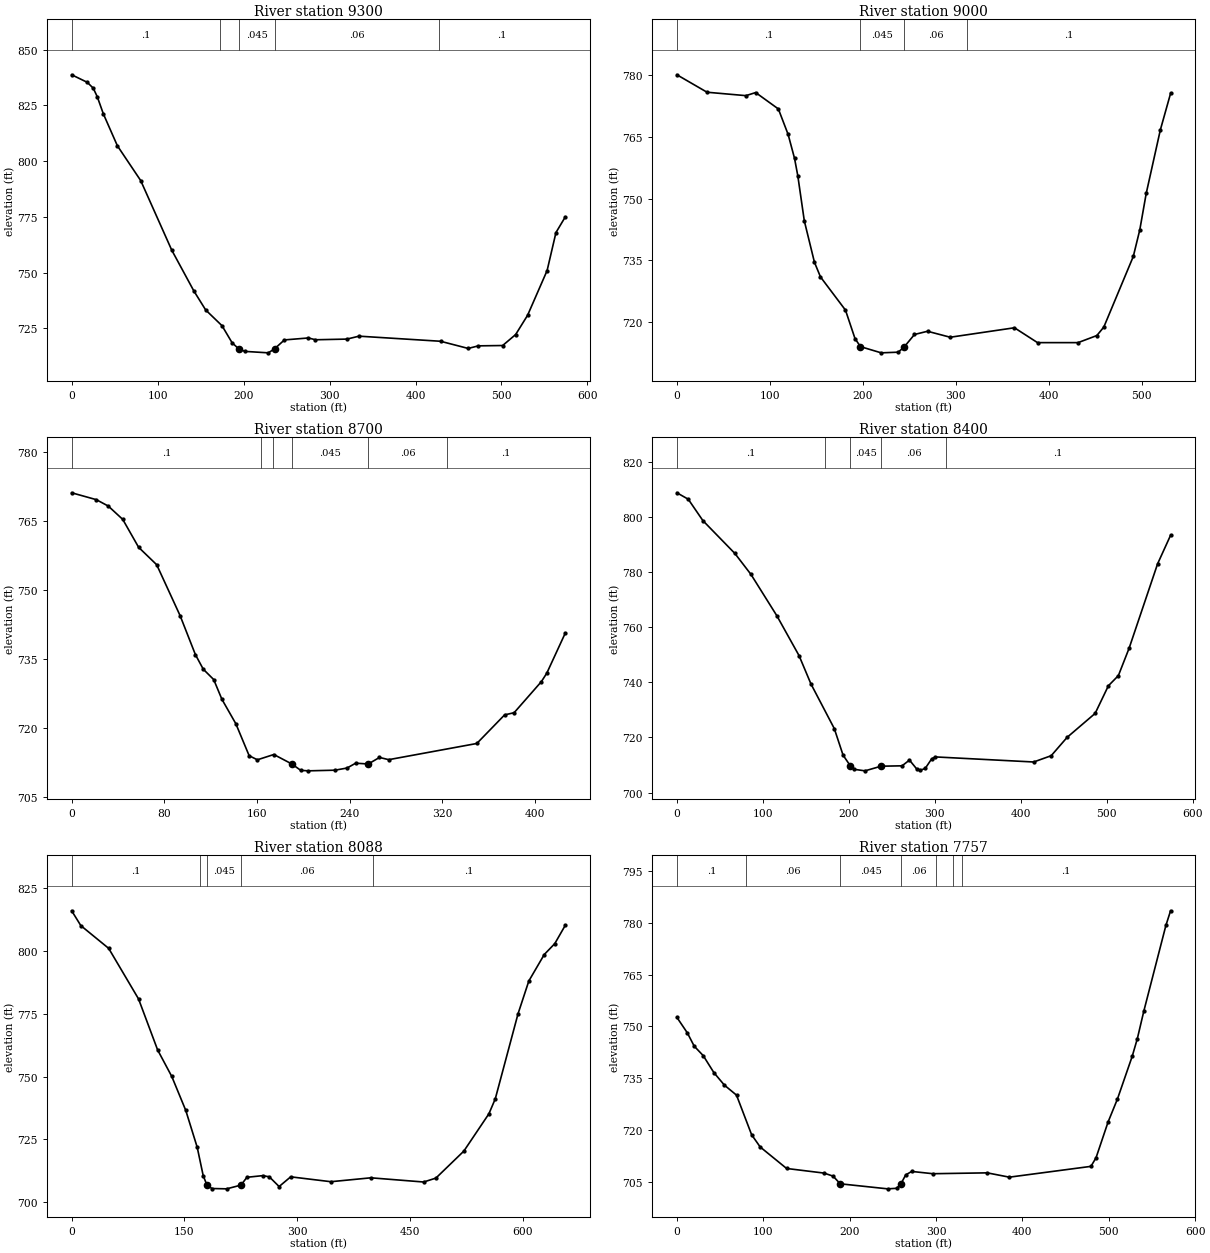
Type RM Length L Ch R = 1 ,9300    ,305.3,300,292.4
XS GIS Cut Line= 6
1619875.23583934464840.6411545871619944.91713043464893.563620925
1620004.64371701464938.9257349221620084.27905643464999.408553585
1620144.78451285465043.7457352581620337.79303625465180.957803877
#Sta/Elev= 30
       0  838.71    18.1  835.34    25.1  832.71    29.8  828.86    36.9  821.16
    53.2  806.88    80.3  791.31   116.4  760.14   142.1  741.86   155.9  733.31
   174.9  726.25   186.6  718.64  194.17715.9278   201.5  714.74   228.8  714.09
  236.14715.9255   247.5  719.88   275.5  720.76   283.6  719.95   320.2  720.25
   334.3  721.56   429.1  719.28   461.3  716.06   473.1  717.22   501.4  717.37
   516.5  722.29   530.4  730.92   553.1  750.96   563.4     768   574.3  775.04
#Mann= 5 ,-1,0
       0      .1       0   172.5     .06       0  194.17    .045       0
  236.14     .06       0  427.51      .1       0
Bank Sta=194.17,236.14
XS Rating Curve= 0 ,0
Exp/Cntr(USF)=0,0
Exp/Cntr=0.3,0.1

Type RM Length L Ch R = 1 ,9000    ,295,300,309.6
XS GIS Cut Line= 6
1619739.43657026465176.6821491721619821.78745542465206.255580842
1619892.37392843465231.6042834221619986.48922576465265.402772263
1620057.07569876465290.7514748421620237.07533201465361.502089424
#Sta/Elev= 30
       0   780.1    32.4  775.86    74.2  775.03    84.7  775.78   109.1   771.8
   119.6  765.61   126.5  759.79     130  755.58     137  744.62   147.9  734.56
   154.4  730.99   181.3  722.92   191.5  716.03  197.39714.0557   219.7  712.55
   238.1  712.71  244.68714.0555   255.5  717.01   269.5  717.79   293.9  716.34
     363  718.64   387.8  715.03   431.4  715.03   451.6  716.75   459.1  718.81
   490.8  735.96   497.8  742.44   504.7  751.28   519.9  766.71   530.9  775.57
#Mann= 4 ,-1,0
       0      .1       0  197.39    .045       0  244.68     .06       0
   312.5      .1       0
Bank Sta=197.39,244.68
XS Rating Curve= 0 ,0
Exp/Cntr(USF)=0,0
Exp/Cntr=0.3,0.1

Type RM Length L Ch R = 1 ,8700    ,289.7,300,312.8
XS GIS Cut Line= 6
  1619633.266507465378.1630454211619696.93895184465439.813840762
1619758.43259525465482.7497785091619840.42455725465539.997695506
1619901.91820067465582.9339613321619973.66116743465633.026052758
#Sta/Elev= 30
       0  771.15    21.3  769.65    31.6  768.26    44.1  765.36    57.8  759.29
    73.4   755.5    93.6  744.43   106.8  735.96   113.6  732.78   122.6  730.53
   129.7  726.23   141.7  720.93   153.2  713.97   160.3  713.08   174.5  714.23
  190.03 712.174   197.7  710.79   204.2  710.68   227.2  710.82   237.7  711.29
   245.1  712.34  256.03712.1746   265.7  713.59   273.7  713.11   349.7  716.63
   373.7  722.85   381.9  723.32   405.4  730.07   410.1  731.92   426.1  740.66
#Mann= 6 ,-1,0
       0      .1       0  163.63     .07       0  173.63     .06       0
  190.03    .045       0  256.03     .06       0  323.63      .1       0
Bank Sta=190.03,256.03
XS Rating Curve= 0 ,0
Exp/Cntr(USF)=0,0
Exp/Cntr=0.3,0.1

Type RM Length L Ch R = 1 ,8400    ,315.5,312.4,308.6
XS GIS Cut Line= 6
1619415.98118043 465502.464962171619472.28815442465569.440878093
1619520.55150934465626.848571673 1619584.9024305465703.392381832
1619633.16578542465760.800075427 1619790.6513084465937.189320746
#Sta/Elev= 30
       0  808.71    13.2  806.37    30.2  798.62    67.4  786.71    86.1  779.11
   116.1  764.17     142  749.67   155.9  739.36     183   723.2   193.2  713.57
   201.8  709.62   206.1  708.43   218.7  707.88   237.4  709.56   261.8   709.7
   270.4  711.78   278.9  708.53   283.2  708.12   288.7  708.75   296.1  712.17
   300.4  712.93   414.8  711.09   435.2  713.37   453.7  720.02   486.3  728.71
   501.7  738.73   513.3  742.41   525.8  752.35   558.9  782.94     574  793.29
#Mann= 5 ,-1,0
       0      .1       0   172.5     .06       0   201.8    .045       0
   237.4     .06       0   312.5      .1       0
Bank Sta=201.8,237.4
XS Rating Curve= 0 ,0
Exp/Cntr(USF)=0,0
Exp/Cntr=0.3,0.1

Type RM Length L Ch R = 1 ,8088    ,337.1,331.1,322.4
XS GIS Cut Line= 2
1619165.32216479465735.8542319571619659.40384485466167.766218181
#Sta/Elev= 30
       0  816.02    12.2  810.11    49.2  801.06    88.9  780.93   114.3   760.6
   133.1  750.05   151.7  736.53   166.9  721.86   174.9  710.53  179.86  706.81
   186.5  705.44   206.1  705.31  225.14706.8018     233  709.91   253.9  710.56
   262.7  710.11   275.8  706.23   291.2  710.09   344.6  708.15   397.8   709.7
   467.9  708.03   484.2  709.58   521.4  720.34   554.7  735.19   563.2  741.17
   593.4  774.98   607.8  788.08   628.3  798.61   642.3  802.95   656.3  810.27
#Mann= 5 ,-1,0
       0      .1       0     170     .06       0  179.86    .045       0
  225.14     .06       0     400      .1       0
Bank Sta=179.86,225.14
XS Rating Curve= 0 ,0
Exp/Cntr(USF)=0,0
Exp/Cntr=0.3,0.1

Type RM Length L Ch R = 1 ,7757    ,252.2,256.5,263
XS GIS Cut Line= 2
1619003.15228167466093.1632558411619539.29171228466291.469710927
#Sta/Elev= 30
       0  752.62    12.1  748.13      20   744.3    30.5  741.54    42.8  736.63
      55     733      69  730.11    86.5  718.64    96.4   715.1     127  708.87
   170.4  707.53   180.9  706.64  189.06704.4293   243.9  702.97   254.4  703.12
  259.41704.4273   264.9  707.01   271.9  708.01   296.4  707.35   359.3   707.6
   384.9  706.35   479.4  709.48   485.3  711.97   499.2   722.3   510.1     729
   527.2  741.37   533.1  746.45   540.7  754.52   566.2  779.27   571.6   783.5
#Mann= 7 ,-1,0
       0      .1       0      80     .06       0  189.06    .045       0
  259.41     .06       0     300      .1       0     320     .06       0
     330      .1       0
Bank Sta=189.06,259.41
XS Rating Curve= 0 ,0
Exp/Cntr(USF)=0,0
Exp/Cntr=0.3,0.1

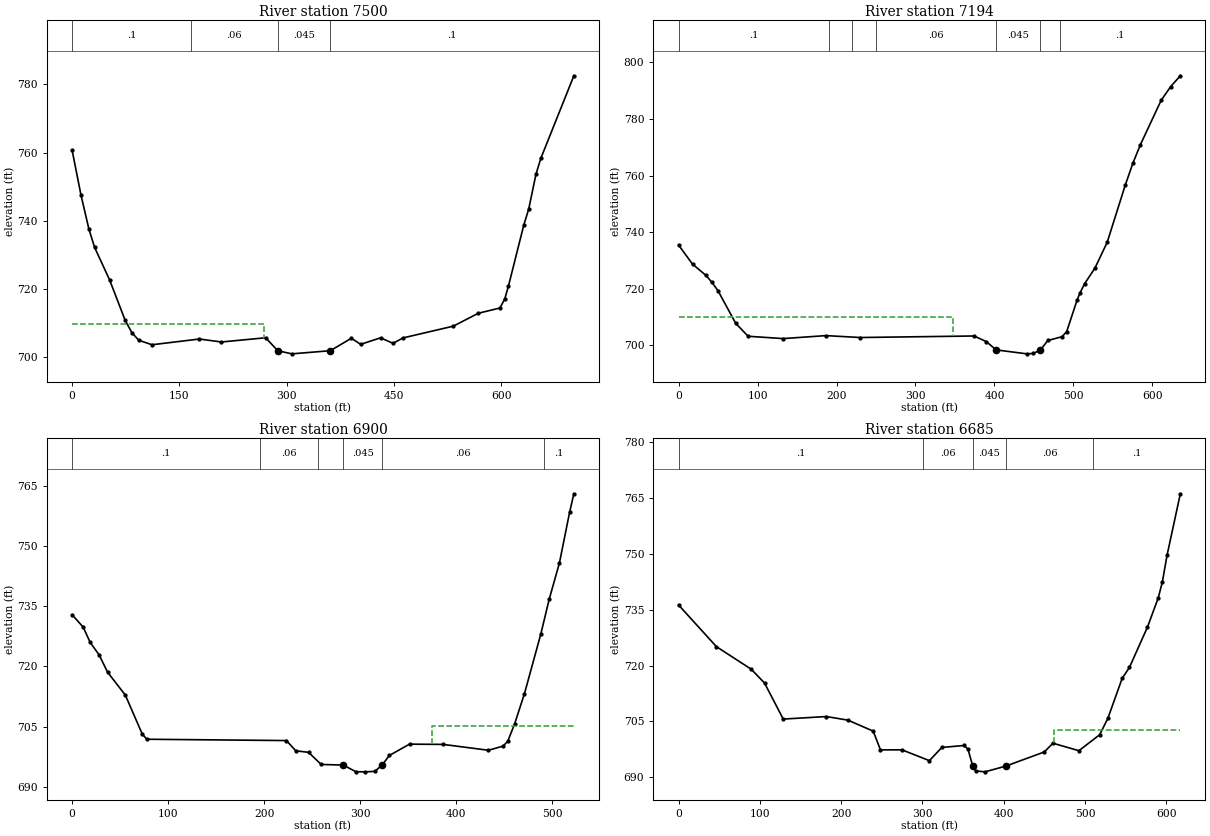
Type RM Length L Ch R = 1 ,7500    ,296.7,306.5,317.4
XS GIS Cut Line= 6
1618842.93537982466215.8452253231618926.55978912466295.848165669
1619055.71812142466376.8592107591619143.22155534466425.265281916
1619330.02728757466495.688236619 1619460.7116626466525.102066527
#Sta/Elev= 30
       0  760.76    12.5  747.53    23.6  737.55    31.5  732.25    52.5   722.7
    74.2  710.91    83.7  707.23    93.3  705.04   111.8  703.72     178   705.4
   208.9  704.53   270.8  705.77  287.61701.9738   307.4  701.06  361.16 701.974
   390.7  705.63   403.6  703.84   431.4  705.75   448.9  704.14     463  705.73
   533.3  709.17   568.1  712.94   598.4  714.49   605.1  717.11   610.2  720.81
   631.8  738.79   638.7   743.5   648.8  753.64   655.6  758.31   701.8  782.49
#Mann= 4 ,-1,0
       0      .1       0  165.73     .06       0  287.61    .045       0
  361.16      .1       0
#XS Ineff= 2 , 0
          268.59  709.78
Permanent Ineff=
       F       F
Bank Sta=287.61,361.16
XS Rating Curve= 0 ,0
Exp/Cntr(USF)=0,0
Exp/Cntr=0.3,0.1

Type RM Length L Ch R = 1 ,7194    ,280.5,293.5,315.8
XS GIS Cut Line= 6
1618742.77260186466315.4647619331618877.29295334466556.608195096
1618932.12388043466628.2399415821618997.54763409466712.186296001
1619035.69782026466776.7583453361619080.20626143 466852.09251225
#Sta/Elev= 30
       0  735.48    17.7  728.72    34.8  724.72    42.3  722.27    49.9  719.35
    72.4  707.79    88.1  703.23   132.5  702.41   186.5  703.46     230  702.79
   374.1  703.33   389.7  701.35  402.06698.4169   440.9  697.02   449.3  697.15
  458.24698.4175   467.6  701.74   485.5  703.07   491.4  704.86   504.6  716.02
   508.4  718.62   514.2  721.85   527.3  727.37   542.7  736.44   565.5  756.57
   575.2  764.36   584.8  770.96     611  786.59   623.1  791.46   635.3  795.28
#Mann= 7 ,-1,0
       0      .1       0     190     .06       0     220      .1       0
     250     .06       0  402.06    .045       0  458.24     .06       0
  482.76      .1       0
#XS Ineff= 2 , 0
          347.22  710.17
Permanent Ineff=
       F       F
Bank Sta=402.06,458.24
XS Rating Curve= 0 ,0
Exp/Cntr(USF)=0,0
Exp/Cntr=0.3,0.1

Type RM Length L Ch R = 1 ,6900    ,227.6,214.6,199.8
XS GIS Cut Line= 6
1618620.97385993466384.5545653581618661.06221373466471.923157024
1618674.58272883466631.5178221761618680.06073625 466731.36768809
1618684.17030808466806.2550055091618708.74703059466894.088163167
#Sta/Elev= 30
       0  732.91    11.6  729.82    18.8  726.03    28.3  722.84    36.9   718.6
    55.5  712.85      73  703.18    77.8  701.85   223.2  701.52     233  698.96
   246.2  698.59   259.4  695.56   282.4  695.41   295.5  693.75   305.4  693.72
   315.2  693.83  322.85695.4207   330.4  697.81   351.4  700.63   386.5  700.56
   433.6   699.1   448.9  700.15   453.7  701.37   460.9  705.74   471.1  713.26
   488.1   728.1   496.8  736.76   507.5  745.85   518.1   758.5   522.5  763.08
#Mann= 6 ,-1,0
       0      .1       0  196.13     .06       0  256.13      .1       0
   282.4    .045       0  322.85     .06       0  491.29      .1       0
#XS Ineff= 2 , 0
                           374.3          705.08
Permanent Ineff=
       F       F
Bank Sta=282.4,322.85
XS Rating Curve= 0 ,0
Exp/Cntr(USF)=0,0
Exp/Cntr=0.3,0.1

Type RM Length L Ch R = 1 ,6685    ,174.1,171.8,161.9
XS GIS Cut Line= 3
1618369.74823955466443.6930481561618358.10097923466623.696162089
1618652.45901261466946.642925323
#Sta/Elev= 30
       0  736.26    46.6  725.07    89.4  719.01   105.8   715.3   128.8  705.63
   181.9  706.31   208.4  705.34   239.5  702.39   248.4  697.36   274.8  697.38
   308.6  694.47   323.9  698.02   351.4  698.54   356.1  697.53  361.93693.0142
   365.4  691.72     377  691.47   402.6693.0133   449.9   696.8   460.6  699.15
   492.5  697.14   518.1  701.43   528.1   705.8   545.8  716.57   554.7  719.49
   576.9  730.33   590.2  738.19   595.3  742.53   600.9  749.53   617.3  766.09
#Mann= 5 ,-1,0
       0      .1       0  300.38     .06       0  361.93    .045       0
   402.6     .06       0  510.38      .1       0
#XS Ineff= 2 , 0
                          461.44          702.63
Permanent Ineff=
       F       F
Bank Sta=361.93,402.6
XS Rating Curve= 0 ,0
Exp/Cntr(USF)=0,0
Exp/Cntr=0.3,0.1