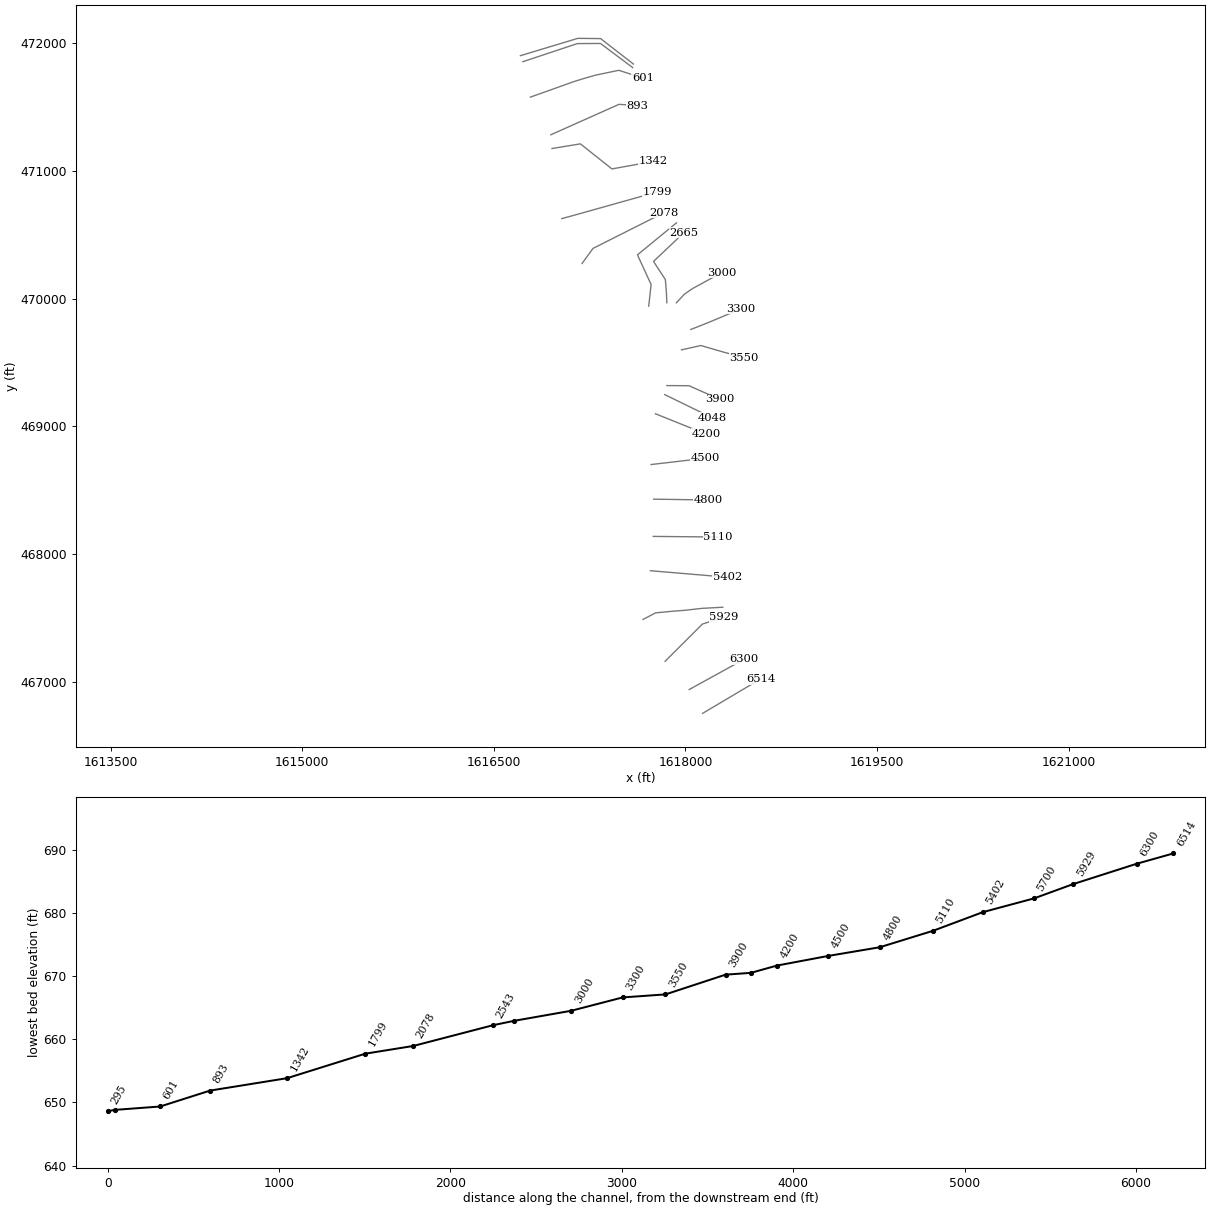
HEC-RAS study WhtstneCrk.prj: WhtstneCrk

--- WhtstneCrk.g01 (geometry) --- (continued)

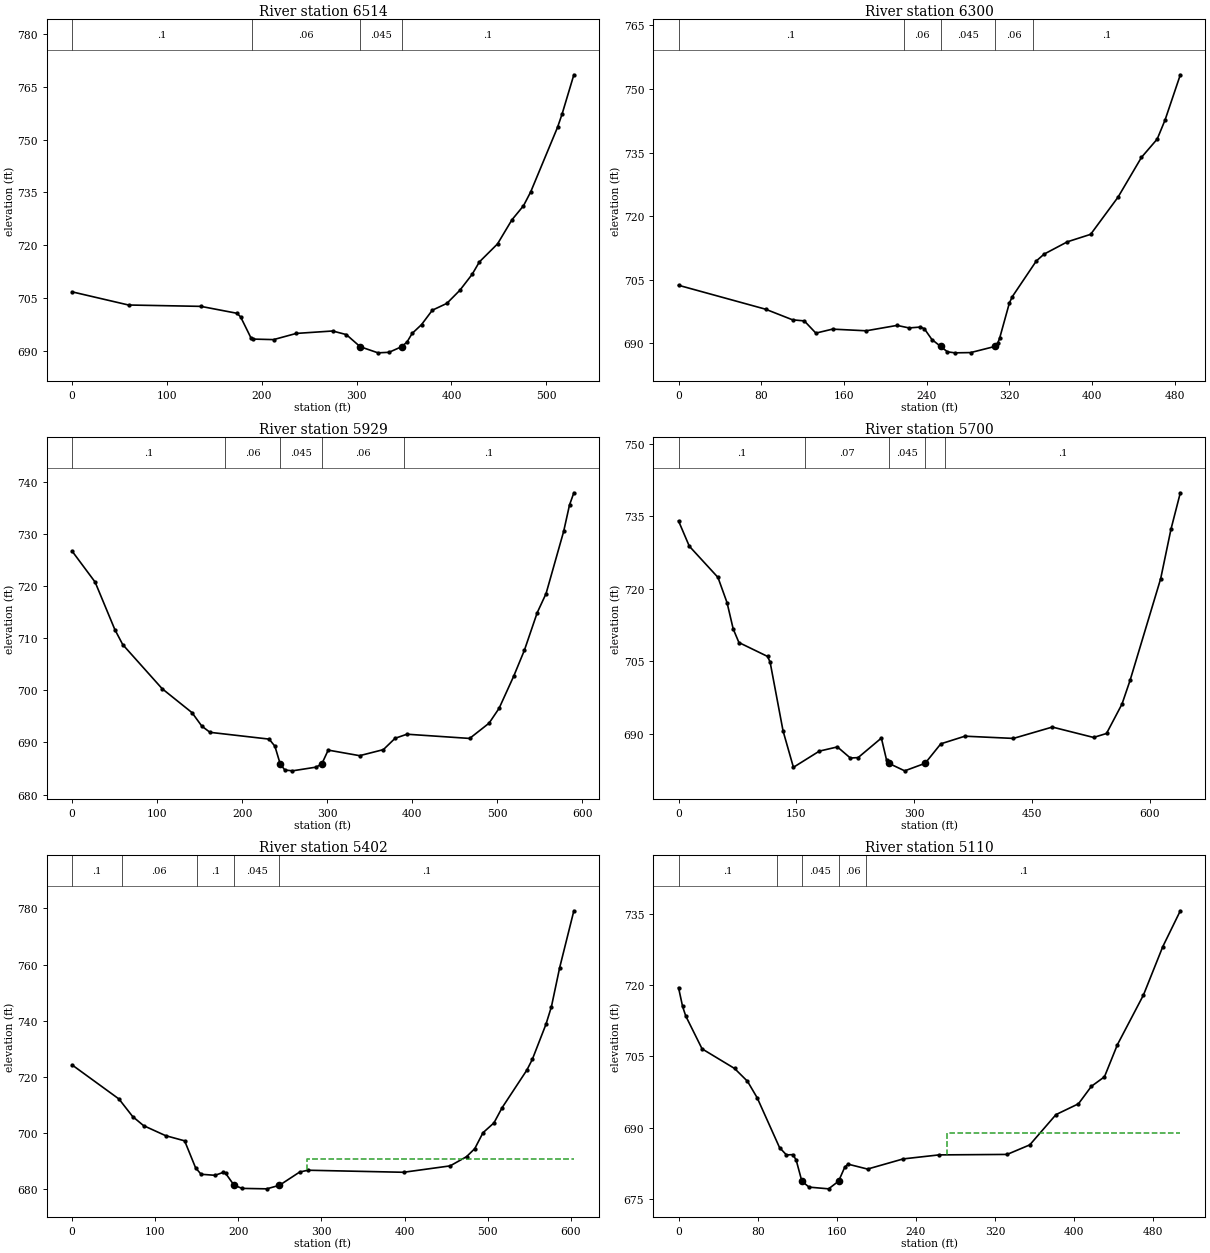
Type RM Length L Ch R = 1 ,6514    ,212.5,213.6,209.2
XS GIS Cut Line= 2
1618134.09902534466752.3730225661618589.22591348467021.928843567
#Sta/Elev= 30
       0  706.75    59.5  703.01   135.8  702.62   173.9  700.65   177.7  699.62
   188.5  693.71   190.9  693.32   212.4  693.17   236.4  694.93   274.7  695.62
   289.1   694.6  303.77691.1445   322.5  689.41   334.1  689.56  347.36691.1438
   353.1  692.48   358.5  694.92   368.4  697.43   379.8  701.53   395.1  703.47
   408.8  707.19   421.8  711.74   429.4  715.26   448.5  720.37   463.7  727.22
   475.9  731.22   483.5  735.17   511.8  753.53   516.6  757.31     529  768.46
#Mann= 4 ,-1,0
       0      .1       0     190     .06       0  303.77    .045       0
  347.36      .1       0
Bank Sta=303.77,347.36
XS Rating Curve= 0 ,0
Exp/Cntr(USF)=0,0
Exp/Cntr=0.3,0.1

Type RM Length L Ch R = 1 ,6300    ,365,370.9,379.6
XS GIS Cut Line= 6
1618029.60343476466938.9024472311618159.21663359467010.478022262
 1618224.9350061467046.6180418431618312.55950275467094.804953337
1618378.27787526467130.944644839  1618454.024771467174.789373428
#Sta/Elev= 30
       0  703.71    84.2  698.07   110.4  695.56   121.7  695.31   132.9  692.43
     149  693.37   181.6  692.98   211.5  694.25   223.1  693.65     234  693.86
   237.8  693.49   245.2  690.92  253.68689.2823   260.2  688.02   267.4  687.78
   282.7  687.84  306.04689.2805   308.9  690.07   310.8  691.28   320.1  699.47
   322.9  700.99   346.3  709.46   353.8  711.06   376.3  713.96   398.8  715.72
   425.3  724.48     448  733.87   463.2  738.17   470.8  742.66   485.6  753.34
#Mann= 5 ,-1,0
       0      .1       0  218.06     .06       0  253.68    .045       0
  306.04     .06       0  343.06      .1       0
Bank Sta=253.68,306.04
XS Rating Curve= 0 ,0
Exp/Cntr(USF)=0,0
Exp/Cntr=0.3,0.1

Type RM Length L Ch R = 1 ,5929    ,243.1,229.1,209.4
XS GIS Cut Line= 3
1617840.80847335467160.0827263611618132.49580209467451.180086108
1618301.71195527467507.146453493
#Sta/Elev= 30
       0  726.74    27.1  720.79    50.3  711.68    59.6  708.79     106  700.32
   141.1  695.73   152.7  693.13   162.3  691.95   231.8  690.65   238.6  689.29
   244.7685.9596   250.2  684.72   259.3  684.56   287.4  685.28  293.98 685.958
   301.3  688.54   338.3  687.47   366.2  688.63     380  690.81     394  691.59
   467.7  690.78   490.5   693.7   502.3  696.55   519.6  702.75   532.1   707.7
   547.2  714.92   557.6  718.58   578.3  730.52   585.2   735.6   590.3  737.93
#Mann= 5 ,-1,0
       0      .1       0     180     .06       0   244.7    .045       0
  293.98     .06       0     390      .1       0
Bank Sta=244.7,293.98
XS Rating Curve= 0 ,0
Exp/Cntr(USF)=0,0
Exp/Cntr=0.3,0.1

Type RM Length L Ch R = 1 ,5700    ,301,298.1,292.9
XS GIS Cut Line= 6
1617667.92036203467487.7992387821617766.13276579467539.093433837
1617894.15318733467551.5008903441617993.85672809467559.194444507
1618128.63517557467574.3763736091618292.34805397467583.460969334
#Sta/Elev= 30
       0     734    13.7  728.78    50.2  722.32    61.8  717.08    69.6  711.66
    76.9  708.84   113.3  705.97   116.6   704.8   133.1  690.55   146.3  683.02
   179.3  686.37   202.3  687.24   218.8  684.94   228.7  685.03   258.3  689.07
   264.9  684.53   267.7  683.85     288  682.29     314683.8471     334  687.88
   364.7  689.46   426.4     689     476  691.35   528.5   689.2     545  690.02
   564.7   696.1     575  701.01     614  722.07   627.1   732.3     639  739.83
#Mann= 5 ,-1,0
       0      .1       0   160.8     .07       0   267.7    .045       0
     314     .07       0  339.42      .1       0
Bank Sta=267.7,314
XS Rating Curve= 0 ,0
Exp/Cntr(USF)=0,0
Exp/Cntr=0.3,0.1

Type RM Length L Ch R = 1 ,5402    ,290.6,292.4,298.7
XS GIS Cut Line= 2
1617725.57839325467869.1203338351618327.02951497467818.392999282
#Sta/Elev= 30
       0  724.27    56.4  712.13    72.9  705.87      86  702.64   112.4  699.08
   135.4  697.22   148.6   687.6   155.2  685.31     172  684.94   181.5  685.95
   184.8  685.61  194.89681.3899   204.6  680.28   234.2  680.12  249.48681.3906
   273.7  686.09   283.6  686.75   398.8  686.02   454.8   688.3   474.5  691.58
   484.4  694.44   494.3  700.11   507.5  703.62   517.3  709.03     547  722.39
   553.6  726.22     570  738.71   576.6     745   586.5  758.89   603.6  779.18
#Mann= 5 ,-1,0
       0      .1       0      60     .06       0     150      .1       0
  194.89    .045       0  249.48      .1       0
#XS Ineff= 2 , 0
                          282.53          690.89
Permanent Ineff=
       F       F
Bank Sta=194.89,249.48
XS Rating Curve= 0 ,0
Exp/Cntr(USF)=0,0
Exp/Cntr=0.3,0.1

Type RM Length L Ch R = 1 ,5110    ,306.8,309.5,306.3
XS GIS Cut Line= 2
1617748.18533412468137.818943426 1618255.5021841 468132.98369894
#Sta/Elev= 30
       0  719.48     4.1  715.52     7.3  713.51    23.8   706.6    56.6  702.48
    69.7  699.78    79.5  696.31   102.1  685.84   109.1  684.28   115.6  684.35
   118.9  683.23  124.68 678.749     132  677.51   151.7  677.15  161.78678.7522
   168.1  681.73   171.4  682.34   191.1  681.31   227.2  683.45   263.3  684.29
   332.2  684.39   355.1   686.4   381.6  692.77   404.3  695.04   417.4  698.72
   430.6  700.72   443.7  707.48     470  717.92   489.6  728.12   507.3  735.65
#Mann= 5 ,-1,0
       0      .1       0     100     .06       0  124.68    .045       0
  161.78     .06       0     190      .1       0
#XS Ineff= 2 , 0
                          271.62          688.87
Permanent Ineff=
       F       F
Bank Sta=124.68,161.78
XS Rating Curve= 0 ,0
Exp/Cntr(USF)=0,0
Exp/Cntr=0.3,0.1

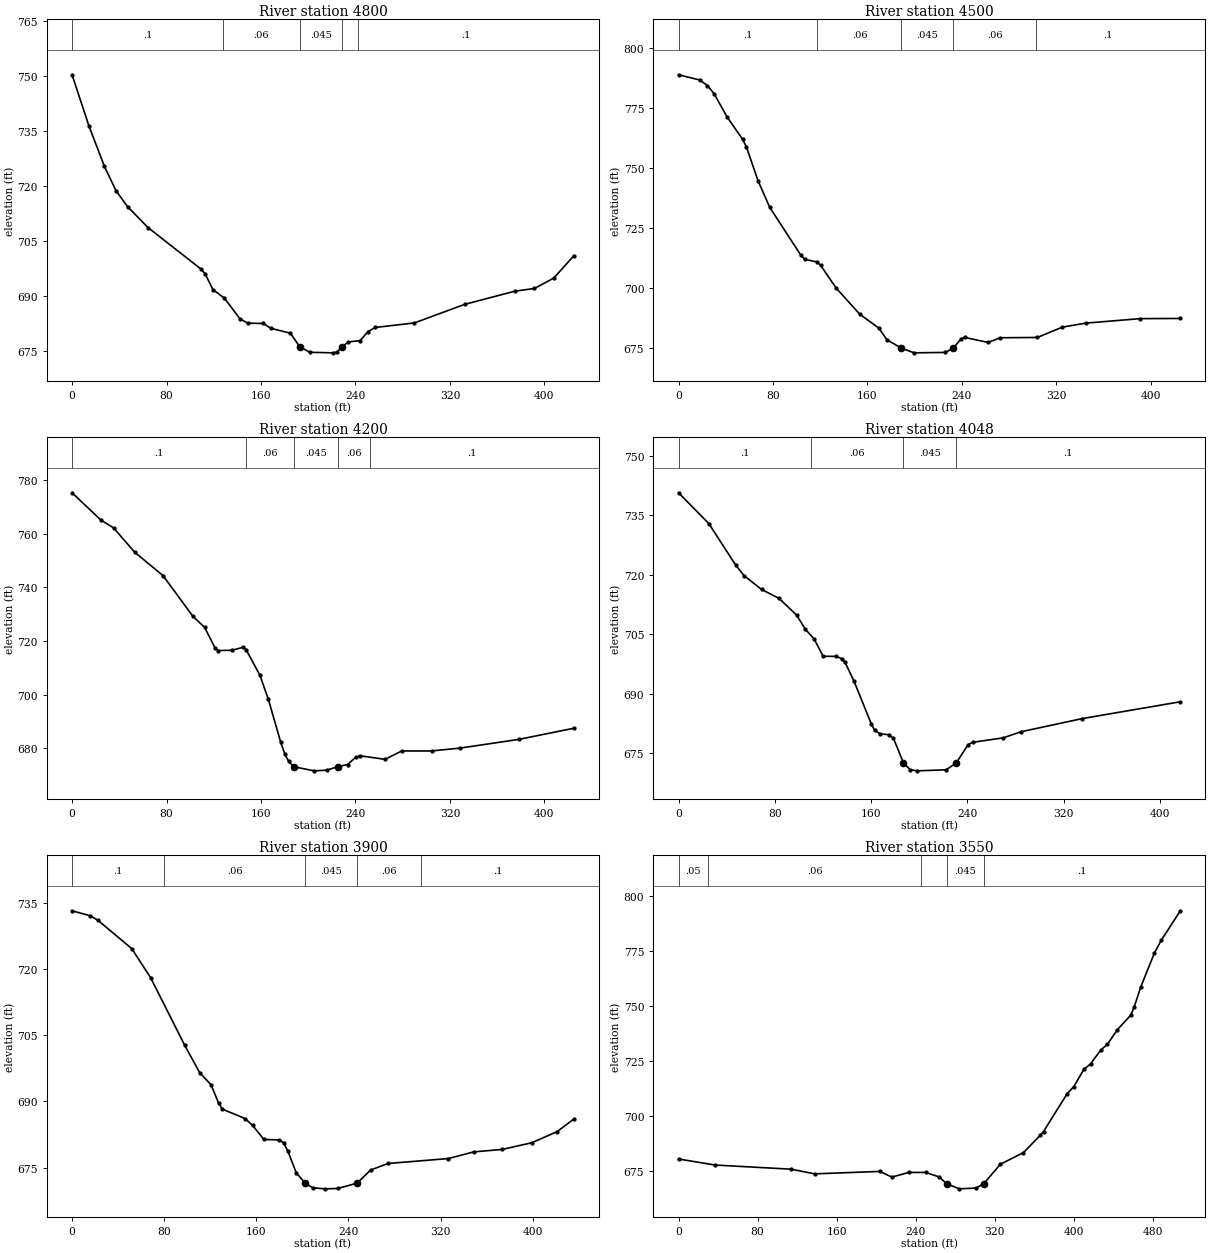
Type RM Length L Ch R = 1 ,4800    ,297.2,300,302.3
XS GIS Cut Line= 6
1617751.10688551468429.3646201791617838.59686801  468428.0391635
1617913.58818784 468426.903010921618013.57683301468425.387922093
1618088.56815284468424.2517695131618176.05813535468422.926312834
#Sta/Elev= 30
       0  750.35    14.3   736.4    27.4  725.38    37.2  718.77    47.1  714.37
    64.3  708.72   109.4  697.34   112.7  696.09   119.3   691.8   129.1  689.45
   142.2  683.84   148.8  682.66   161.9  682.56   168.5  681.24   184.9  679.91
  192.72676.2787   201.3  674.71     221  674.56   224.3  674.78  228.93676.2786
     234  677.52     244  677.91   250.5  680.27   256.6  681.47   289.9  682.71
   332.5  687.77   375.2  691.38   391.6   692.1     408  694.94     425  701.03
#Mann= 5 ,-1,0
       0      .1       0   127.5     .06       0  192.72    .045       0
  228.93     .06       0   242.5      .1       0
Bank Sta=192.72,228.93
XS Rating Curve= 0 ,0
Exp/Cntr(USF)=0,0
Exp/Cntr=0.3,0.1

Type RM Length L Ch R = 1 ,4500    ,311.7,300,292.2
XS GIS Cut Line= 6
 1617731.2250355 468700.37785767  1617818.136279 468710.51267992
1617892.63153684 468719.199342341617991.95810984 468730.78199634
1618066.45336768 468739.468658761618153.36461118468749.603152916
#Sta/Elev= 30
       0  788.77    17.9  786.61    24.5  784.29    30.2  780.87      41  771.32
    54.2  762.01    57.5  758.77    67.4  744.64    77.3  733.63   103.7  713.69
     107  712.04     117     711   120.3  709.58   133.5  700.13   153.3  689.33
   169.8  683.41   176.4  678.65  188.83675.1273   199.5  673.19     226  673.37
  232.78 675.128   239.2     679   242.5  679.58   262.3   677.5   272.2  679.46
   303.9  679.58     325  683.86   344.9  685.54   391.1  687.41     425  687.48
#Mann= 5 ,-1,0
       0      .1       0   117.5     .06       0  188.83    .045       0
  232.78     .06       0   302.5      .1       0
Bank Sta=188.83,232.78
XS Rating Curve= 0 ,0
Exp/Cntr(USF)=0,0
Exp/Cntr=0.3,0.1

Type RM Length L Ch R = 1 ,4200    ,153.2,151.8,150.7
XS GIS Cut Line= 6
1617765.47693551 469097.692023681617846.66476525469065.061183423
1617916.25419301469037.0914230941618009.04009667468999.798846751
 1618078.6298525468971.8290864231618159.81768225468939.198246166
#Sta/Elev= 30
       0  775.24    24.6  765.01    35.2  762.15    52.9  753.16    77.1  744.34
   102.4  729.19   112.3   725.1   121.1  717.43   123.6  716.48   135.5  716.57
   144.9   717.7   147.5  716.69     159  707.36   166.1  698.52   176.7  682.36
   180.2  677.87   183.4  675.29  187.66 673.207     205  671.66   215.6  671.91
  225.16673.2079   233.3  674.01   240.3  676.73   243.9  677.27   265.1  675.94
   279.2  679.06   304.5  679.07   328.7  680.14   378.2  683.36     425  687.53
#Mann= 5 ,-1,0
       0      .1       0   147.5     .06       0  187.66    .045       0
  225.16     .06       0   252.5      .1       0
Bank Sta=187.66,225.16
XS Rating Curve= 0 ,0
Exp/Cntr(USF)=0,0
Exp/Cntr=0.3,0.1

Type RM Length L Ch R = 1 ,4048    ,148.1,148.2,149.6
XS GIS Cut Line= 2
1617837.86990058469247.8141950741618212.60405207 469064.80449318
#Sta/Elev= 30
       0  740.65    25.2  732.87    47.6  722.36    54.4  719.76      69  716.26
    83.6     714    98.2  709.76   105.5  706.18   112.8  703.74   120.1  699.41
     131  699.38     136  698.76   138.4  697.85   145.8  693.16   160.3  682.26
   162.9  680.79   167.6  679.84   174.9  679.62   178.6  678.72  186.93672.5001
   192.4  670.82   198.3  670.51   222.4  670.77   230.8672.4995   240.6   677.1
   244.3   677.7   269.8  678.83   284.4  680.35   335.6   683.7     417  687.93
#Mann= 4 ,-1,0
       0      .1       0     110     .06       0  186.93    .045       0
   230.8      .1       0
Bank Sta=186.93,230.8
XS Rating Curve= 0 ,0
Exp/Cntr(USF)=0,0
Exp/Cntr=0.3,0.1

Type RM Length L Ch R = 1 ,3900    ,347.6,350.2,351.3
XS GIS Cut Line= 5
1617854.65884941469318.5740176791618027.91637126469317.411728591
1618119.33252701469276.8770327571618187.89439775469246.475846842
1618267.88373908469211.007741928
#Sta/Elev= 30
       0  733.14    15.7  732.01    22.3  731.02    51.8  724.59    68.2  718.01
    97.7  702.77   110.8  696.53   120.7  693.76   127.3   689.6   130.5  688.26
   150.2  686.13   156.8  684.57   166.6  681.39     180  681.29   183.9  680.58
   187.5  678.71   194.7  673.85  202.46671.4969   209.1  670.45   219.7  670.22
   230.6   670.3  247.53671.4952   259.3  674.48   274.5  675.96   326.7  677.07
     349  678.59   373.4  679.13   399.3  680.65   421.2  683.16   435.8  686.02
#Mann= 5 ,-1,0
       0      .1       0      80     .06       0  202.46    .045       0
  247.53     .06       0  303.26      .1       0
Bank Sta=202.46,247.53
XS Rating Curve= 0 ,0
Exp/Cntr(USF)=0,0
Exp/Cntr=0.3,0.1

Type RM Length L Ch R = 1 ,3550    ,236.6,249.9,264.6
XS GIS Cut Line= 4
1617968.89717202 469598.128836671618120.80981543469632.077616844
 1618295.0417574469581.4308013061618460.06995329469536.500405716
#Sta/Elev= 30
       0  680.62    36.9  677.89   114.2     676   137.7  673.89   203.9  674.99
     216  672.42   233.1  674.53   250.2  674.54   263.8   672.5  271.34669.4692
   284.3   667.1   301.4  667.46  309.13669.4684   325.9  678.24   349.2   683.5
   366.2   691.3   369.6  693.06   393.4  710.13   400.2  713.42   410.4  721.21
   417.2  723.71   427.3  729.85   434.2  732.58   444.4  739.21     458  745.87
   461.4  749.53   468.2  758.76   481.8  773.89   488.8  779.74   508.1  793.09
#Mann= 5 ,-1,0
       0     .05       0      30     .06       0  245.66      .1       0
  271.34    .045       0  309.13      .1       0
Bank Sta=271.34,309.13
XS Rating Curve= 0 ,0
Exp/Cntr(USF)=0,0
Exp/Cntr=0.3,0.1

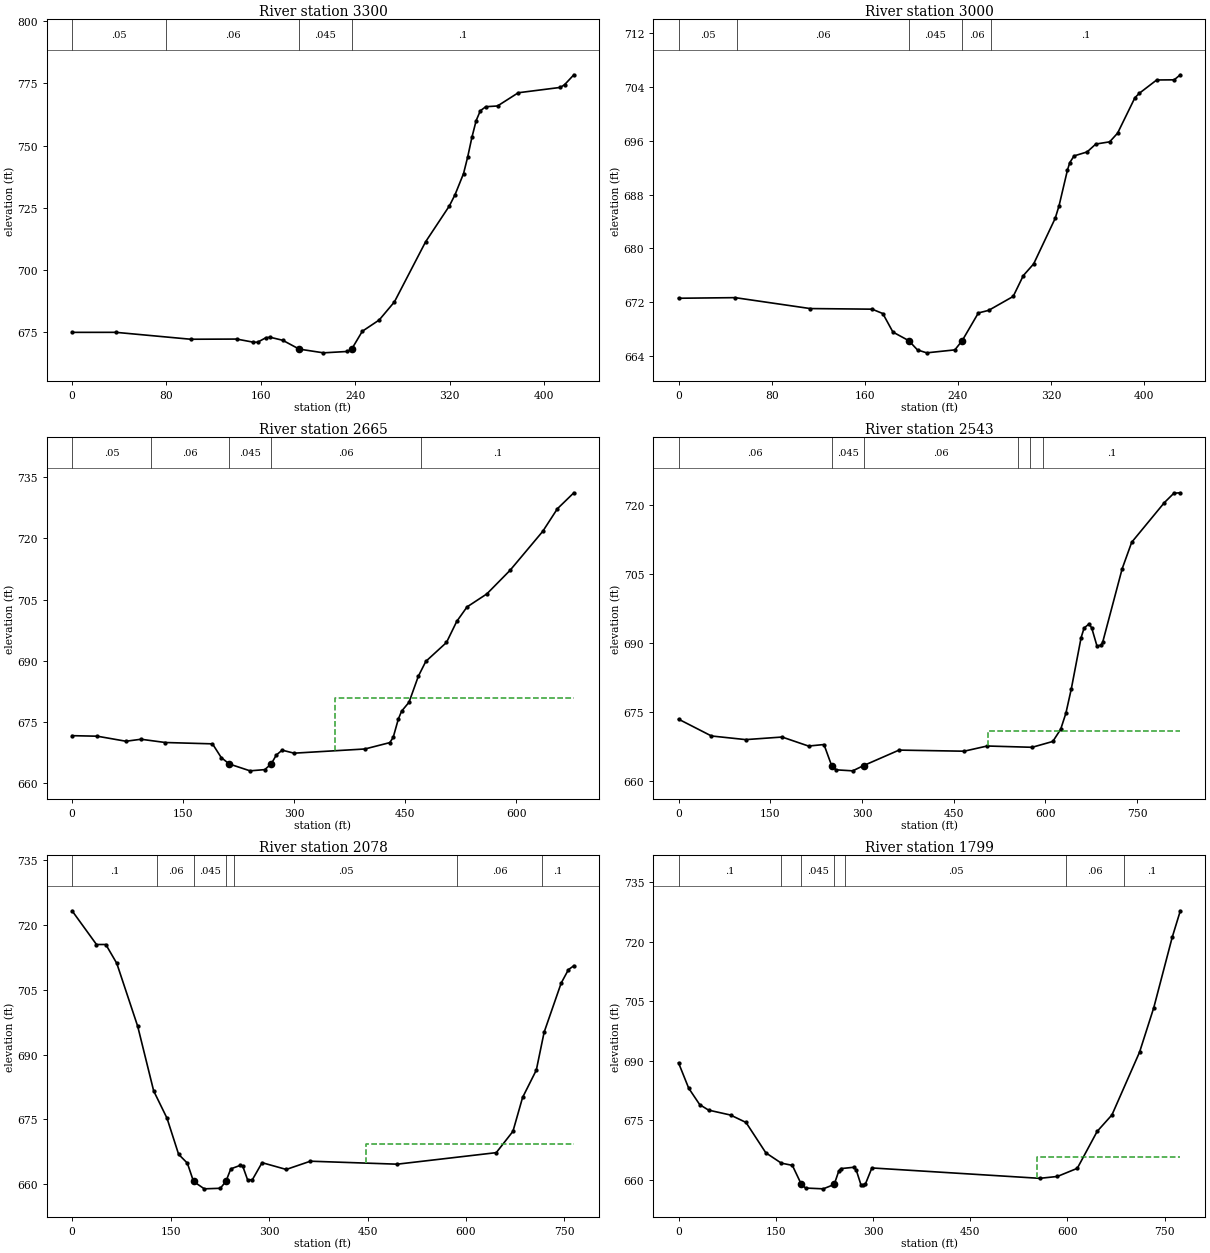
Type RM Length L Ch R = 1 ,3300    ,297.6,299.9,302.1
XS GIS Cut Line= 6
1618042.52789059469757.9876190871618124.15469584469789.908815086
1618193.77660385469818.0718165041618286.06349276469856.651791841
1618354.87306643469886.4519290921618435.24265634469921.092279762
#Sta/Elev= 30
       0  674.86    37.1  674.87   100.5  672.09   139.5  672.16   153.6  670.91
   157.2  670.88   164.2  672.69   167.8   672.9   178.5  671.68   192.5  668.12
   213.1  666.62   233.2  667.17     237  668.12     246   675.3   260.3  679.83
   273.2  687.11   299.6  711.26   319.8  725.74   324.6  730.25   331.8  738.75
   335.3   745.4   338.9  753.34   342.5  760.06     346  763.99   350.6  765.64
   360.6  765.94   378.2  771.26   413.9  773.41   417.5  774.54   425.3  778.49
#Mann= 4 ,-1,0
       0     .05       0      80     .06       0   192.5    .045       0
     237      .1       0
Bank Sta=192.5,237
XS Rating Curve= 0 ,0
Exp/Cntr(USF)=0,0
Exp/Cntr=0.3,0.1

Type RM Length L Ch R = 1 ,3000    ,290,334.8,370.7
XS GIS Cut Line= 6
1617928.92247476 469966.465548591617992.71991934470034.373877332
1618054.64860126470077.4722163381618142.46404243470125.309719086
1618208.32578734 470161.187928171618285.16421634470203.045784086
#Sta/Elev= 30
       0  672.61    48.6   672.7   113.1  671.08   166.3  670.99   175.5  670.34
   184.2  667.59  197.78666.3195   205.3  664.94   213.2  664.51   237.4  664.95
   243.7666.3205   257.6  670.43   266.4  670.81   287.5  672.88   296.2  675.97
   305.1  677.71   323.6  684.47   326.9  686.33   334.1  691.61   336.1  692.73
   339.8  693.73     351  694.32   358.5  695.49   370.4  695.82   377.2  697.11
   392.1  702.37   395.9  703.03   410.8     705   425.8  705.02   431.1  705.77
#Mann= 5 ,-1,0
       0     .05       0      50     .06       0  197.78    .045       0
   243.7     .06       0  268.62      .1       0
Bank Sta=197.78,243.7
XS Rating Curve= 0 ,0
Exp/Cntr(USF)=0,0
Exp/Cntr=0.3,0.1

Type RM Length L Ch R = 1 ,2665    ,129.2,122.1,120.2
XS GIS Cut Line= 5
1617854.52209444469966.7388715111617851.13237554470043.284374941
1617842.80781759470148.7840815931617750.04484511470290.555156961
1617986.89317216470514.605715798
#Sta/Elev= 30
       0  671.55      34  671.42    72.8  670.18    93.1  670.67     126  669.87
   189.7  669.54   201.5  666.18  212.38664.5933   240.4  662.91   260.3  663.21
     269 664.595   275.9  666.79   283.8  667.99   299.9  667.25   395.6  668.28
   429.2  669.84   433.8  671.11   440.8  675.65   445.2  677.57   455.2  679.76
   467.8  686.15   477.9   689.8   505.8  694.44   519.7  699.63   533.6  703.18
   560.3  706.37   591.7  712.17   635.8  721.73   655.7  727.31   677.9  731.22
#Mann= 5 ,-1,0
       0     .05       0  106.62     .06       0  212.38    .045       0
     269     .06       0  471.87      .1       0
#XS Ineff= 2 , 0
                          355.34          680.81
Permanent Ineff=
       F       F
Bank Sta=212.38,269
XS Rating Curve= 0 ,0
Exp/Cntr(USF)=0,0
Exp/Cntr=0.3,0.1

Type RM Length L Ch R = 1 ,2543    ,500.1,464.7,424.4
XS GIS Cut Line= 4
1617712.49804042469940.6372359561617731.30888263470109.600252155
1617624.37353343470341.8565018861617929.80048012470592.465575515
#Sta/Elev= 30
       0  673.46    53.8   669.8   109.9  669.01   169.4  669.57   212.6  667.61
   237.9  667.94   250.4663.3689   257.6  662.44   284.9  662.22  302.84663.3695
   360.7  666.73   467.1  666.49   504.9  667.62   578.4  667.34   612.2  668.61
   625.1  671.26   633.6  674.74   642.5  680.06   658.5  691.18   663.4  693.28
   671.7  694.18     676  693.23   684.5  689.35   691.4  689.56   693.8  690.19
   725.7  706.18   741.3  711.93   794.8  720.56   810.3  722.59   820.8  722.68
#Mann= 6 ,-1,0
       0     .06       0   250.4    .045       0  302.84     .06       0
   555.7      .1       0   575.7     .06       0   595.7      .1       0
#XS Ineff= 2 , 0
                          505.42          670.95
Permanent Ineff=
       F       F
Bank Sta=250.4,302.84
XS Rating Curve= 0 ,0
Exp/Cntr(USF)=0,0
Exp/Cntr=0.3,0.1

Type RM Length L Ch R = 1 ,2078    ,284.3,279.7,274.7
XS GIS Cut Line= 3
1617190.55475599470274.180833983 1617276.6359832470392.557406185
1617828.53073451470670.420567683
#Sta/Elev= 30
       0  723.33    37.2  715.52    51.4  715.52    68.1  711.16     100  696.56
   124.3  681.61   144.6   675.3   162.3  666.93   175.6  664.89  184.99 660.653
   201.4  658.94   225.8  659.07  234.28 660.653   241.8  663.57   256.4  664.39
   260.1  664.13   267.5  660.96   274.8   661.1   289.4     665   326.2  663.43
     363  665.34   495.2  664.65   646.1  667.32   671.5  672.25   686.2   680.1
   707.1  686.43     719   695.2     745  706.59     756  709.69   764.3  710.61
#Mann= 7 ,-1,0
       0      .1       0     130     .06       0  184.99    .045       0
  234.28     .06       0  246.37     .05       0  586.37     .06       0
  716.37      .1       0
#XS Ineff= 2 , 0
                          447.08          669.33
Permanent Ineff=
       F       F
Bank Sta=184.99,234.28
XS Rating Curve= 0 ,0
Exp/Cntr(USF)=0,0
Exp/Cntr=0.3,0.1

Type RM Length L Ch R = 1 ,1799    ,485.6,457,433
XS GIS Cut Line= 3
1617031.75300926470625.6509100051617116.23282717   470648.442203
1617777.38281537470833.999896002
#Sta/Elev= 30
       0  689.49    15.7  683.09    32.7  678.95    46.3  677.57    80.2  676.33
   104.1  674.46   134.7   666.8   158.6   664.2   175.6  663.64  189.57658.8284
   196.1  657.92   223.3  657.72  240.16658.8278   247.2  662.19   250.6  662.82
     271  663.17   274.4  662.35   281.3  658.81   284.7  658.57   288.1  658.84
   298.3  662.99   557.3  660.37   584.5  660.84   615.2  662.89   645.9  672.21
   668.7  676.36   711.3  692.19   733.2  703.38   761.7  721.16   774.2  727.83
#Mann= 7 ,-1,0
       0      .1       0   157.5     .06       0  189.57    .045       0
  240.16     .06       0   257.5     .05       0   597.5     .06       0
   687.5      .1       0
#XS Ineff= 2 , 0
                          552.78          665.75
Permanent Ineff=
       F       F
Bank Sta=189.57,240.16
XS Rating Curve= 0 ,0
Exp/Cntr(USF)=0,0
Exp/Cntr=0.3,0.1

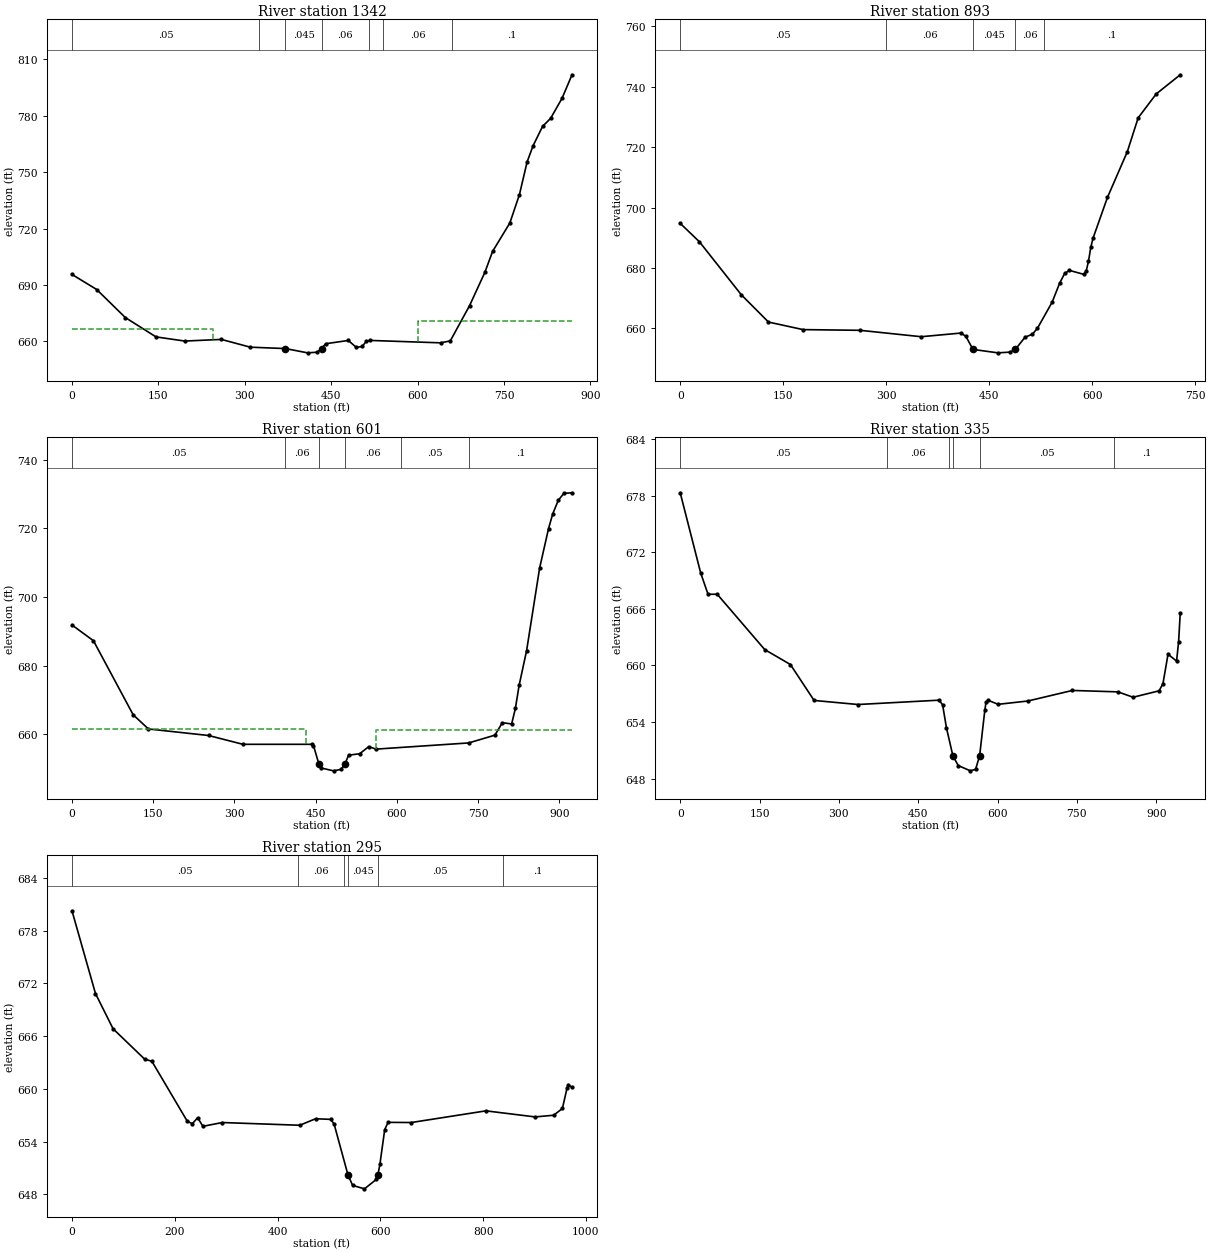
Type RM Length L Ch R = 1 ,1342    ,397.8,448.6,471
XS GIS Cut Line= 4
1616955.35835307471174.4132690551617177.58441966471210.724717844
1617424.50227142471014.6428943861617746.94793666471072.741212448
#Sta/Elev= 30
       0  695.56    42.9  687.54    92.7  672.59   145.9  662.32   195.8  660.11
   259.4  660.98   309.6  656.85  370.63 656.112   408.9  653.84     426  654.18
  433.39656.1132   440.5  658.69   479.7  660.43   493.7  656.73   503.8  657.22
   510.7  659.88     517  660.45   640.2  659.16   656.8  660.21   690.2  678.93
   716.8  696.65   730.2  707.79   760.2  722.95   776.8  738.01   790.2  755.49
   800.5  764.02     817  774.34     831  778.63   850.8  789.29   868.1   801.8
#Mann= 7 ,-1,0
       0     .05       0  325.17     .07       0  370.63    .045       0
  433.39     .06       0  515.17     .05       0  540.48     .06       0
  660.48      .1       0
#XS Ineff= 2 , 0
          244.77  666.65  601.44          670.92
Permanent Ineff=
       F       F
Bank Sta=370.63,433.39
XS Rating Curve= 0 ,0
Exp/Cntr(USF)=0,0
Exp/Cntr=0.3,0.1

Type RM Length L Ch R = 1 ,893     ,296.2,291.9,289.7
XS GIS Cut Line= 3
1616945.81315123 471281.740201491617479.86727051471520.193740338
1617623.05974366471510.790733075
#Sta/Elev= 30
       0  694.75      28  688.65    89.1  671.08   128.6  662.07     179  659.57
   261.8  659.34   351.1  657.22   408.9  658.43   416.1  657.36  426.46653.0148
   462.7  651.88   480.2  652.11  488.19653.0137   502.3  657.06   513.1  658.06
   520.3  659.98   541.8  668.66   552.6  674.88     560  678.17     567  679.18
   588.2  677.85   591.5  679.06   594.7  682.16   598.1  686.84   601.4  689.85
   622.4  703.36   651.3  718.48   667.1  729.69   693.4  737.61   728.4  743.95
#Mann= 5 ,-1,0
       0     .05       0     300     .06       0  426.46    .045       0
  488.19     .06       0     530      .1       0
Bank Sta=426.46,488.19
XS Rating Curve= 0 ,0
Exp/Cntr(USF)=0,0
Exp/Cntr=0.3,0.1

Type RM Length L Ch R = 1 ,601     ,273.9,266,261.3
XS GIS Cut Line= 6
1616786.40247539 471576.76362537  1617128.452619471698.738986924
  1617200.035153471721.1211600011617296.21475068471748.608965918
1617478.18471212471786.6779218311617668.08631714471725.658477371
#Sta/Elev= 30
       0  691.86    39.7  687.26     113   665.7   141.2  661.56   252.2  659.66
   315.8  657.09   442.6  657.09   446.1  656.71   455.8 651.486   459.7  650.21
   483.1  649.36   497.2  649.78  504.63651.4866   510.9  653.92   531.4  654.34
   548.2  656.42   561.6  655.69   732.8  657.49   781.2  659.76   794.9  663.39
   812.1  663.02     819  667.54   825.9  674.28   839.7  684.35   863.8  708.47
   880.3  719.97   887.9  724.18   898.2  728.17   908.6  730.21   923.6  730.38
#Mann= 6 ,-1,0
       0     .05       0  393.15     .06       0   455.8    .045       0
  504.63     .06       0  608.18     .05       0  734.09      .1       0
#XS Ineff= 2 , 0
          432.49  661.65  562.45          661.37
Permanent Ineff=
       F       F
Bank Sta=455.8,504.63
XS Rating Curve= 0 ,0
Exp/Cntr(USF)=0,0
Exp/Cntr=0.3,0.1

Type RM Length L Ch R = 1 ,335     ,40.2,40.3,40.8
XS GIS Cut Line= 4
1616727.96440596471854.1072658941617153.94693632471995.825056938
1617334.97179419471996.7081050251617587.40673754471807.710406682
#Sta/Elev= 30
       0  678.29    38.7  669.79    52.6  667.53    69.9  667.54   159.8  661.67
   208.3  660.09   253.1  656.28   336.1  655.85   489.5  656.31   496.1  655.81
   503.3  653.38  515.48 650.416   525.6  649.38   548.6  648.82   558.4  648.98
  566.05650.4182   575.8  655.22   578.1  656.08   581.4  656.31   601.1  655.87
   657.1  656.22   741.4  657.34   827.5  657.19   856.2  656.62   905.3   657.3
   912.6  658.05   922.2  661.18   938.4  660.45   942.2   662.5   945.3  665.55
#Mann= 6 ,-1,0
       0     .05       0     390     .06       0  508.94     .05       0
  515.48    .045       0  566.05     .05       0  819.96      .1       0
Bank Sta=515.48,566.05
XS Rating Curve= 0 ,0
Exp/Cntr(USF)=0,0
Exp/Cntr=0.3,0.1

Type RM Length L Ch R = 1 ,295     ,,,
XS GIS Cut Line= 4
1616707.82969923471901.0218254911617157.92065271472036.886792991
 1617335.9546112472034.7789416991617592.45642999471835.739747326
#Sta/Elev= 30
       0  680.27    45.7  670.85      80  666.83   141.7  663.36   155.4  663.14
   224.5  656.29   234.2  656.03   244.5   656.7   254.8  655.73   292.5  656.16
   443.3  655.85   473.9  656.59   503.5  656.52     510  655.99  536.98650.1971
   546.1     649   569.1  648.61   592.1  649.68  595.28650.1973   599.2  651.44
   608.5  655.36     615  656.18   660.2  656.16   805.5  657.49   901.1   656.8
   937.2  656.99   954.2  657.76   963.3   660.1   965.9   660.4   972.9  660.18
#Mann= 6 ,-1,0
       0     .05       0     440     .06       0  530.15     .05       0
  536.98    .045       0  595.28     .05       0   838.2      .1       0
Bank Sta=536.98,595.28
XS Rating Curve= 0 ,0
Exp/Cntr(USF)=0,0
Exp/Cntr=0.3,0.1
LCMann Table=0

Chan Stop Cuts=-1
Use User Specified Reach Order=0
Composite Channel Slope=5